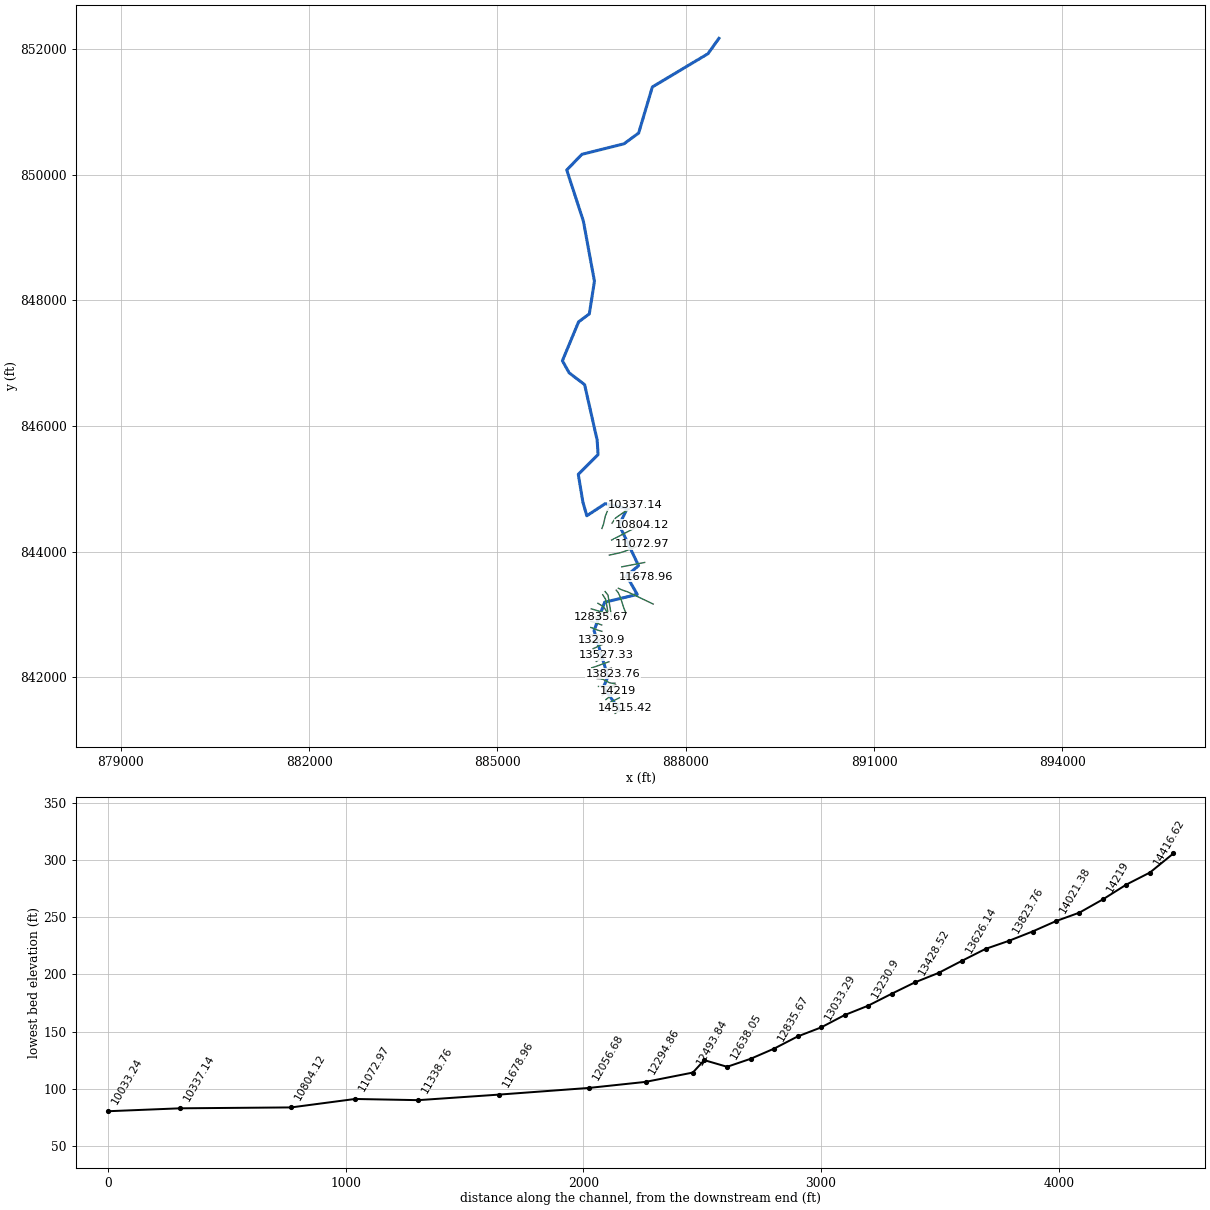
--- 16643_ras.prj (project) ---

Proj Title=16643
Current Plan=p01
Default Exp/Contr=0.3,0.1
English Units
Geom File=g01
Flow File=f01
Plan File=p01
Y Axis Title=Elevation
X Axis Title(PF)=Main Channel Distance
X Axis Title(XS)=Station
BEGIN DESCRIPTION:
RFD model 16643 exported to HEC-RAS
END DESCRIPTION:

--- 16643_ras.p01 (plan) ---

Plan Title=Plan 01
Program Version=4.10
Short Identifier=Plan 01
Geom File=g01
Flow File=f01
Subcritical Flow
Calc Critical at every XS
Secant Critical Depth

--- 16643_ras.f01 (steady flow) ---

Flow Title=Flow 01
Program Version=5.01
Number of Profiles= 6
Profile Names=10yr,25yr,50yr,100yr,100plus,500yr
River Rch & RM=16643,50,14515.42
 1227.97 1636.91 1964.74 2174.79  3175.2  3440.2
River Rch & RM=16643,50,14317.81
 1232.32 1643.22 1972.73 2184.05 3188.71 3454.18
River Rch & RM=16643,50,   14219
 1235.83 1648.25 1979.05 2191.33 3199.34 3465.05
River Rch & RM=16643,50,14021.38
 1243.29 1658.98 1992.55 2206.88 3222.05 3488.28
River Rch & RM=16643,50,13823.76
 1245.88 1662.66 1997.15 2212.14 3229.73 3496.01
River Rch & RM=16643,50,13724.95
 1248.22 1666.08  2001.5 2217.21 3237.13 3503.74
River Rch & RM=16643,50,13626.14
 1251.58 1671.19 2008.13 2225.04 3248.56 3516.09
River Rch & RM=16643,50,13428.52
 1412.38 1888.57 2271.69 2518.97  3677.7  3917.5
River Rch & RM=16643,50,13329.71
 1414.85 1892.32 2276.55 2524.71 3686.08 3926.37
River Rch & RM=16643,50, 13230.9
 1417.36  1896.1 2281.44 2530.47 3694.49 3935.23
River Rch & RM=16643,50,13132.09
 1419.45 1899.26 2285.51 2535.27 3701.49  3942.6
River Rch & RM=16643,50,13033.29
 1421.12 1901.78 2288.77  2539.1 3707.09  3948.5
River Rch & RM=16643,50,12934.48
 1423.21 1904.92 2292.84  2543.9 3714.09 3955.86
River Rch & RM=16643,50,12835.67
 1424.47 1906.81 2295.28 2546.77 3718.29 3960.28
River Rch & RM=16643,50,12736.86
  1425.3 1908.07  2296.9 2548.69 3721.09 3963.22
River Rch & RM=16643,50,12638.05
 1429.48 1914.37 2305.04 2558.27 3735.07 3977.92
River Rch & RM=16643,50,12294.86
 1433.45 1920.45 2312.97 2567.68 3748.81  3992.6
River Rch & RM=16643,50,12056.68
 1490.16 2005.43 2422.53 2696.49 3936.88 4188.79
River Rch & RM=16643,50,11678.96
 1756.55 2404.38 2937.22 3302.38 4821.48 5097.53
River Rch & RM=16643,50,11338.76
 1758.42 2407.42 2941.33 3307.39 4828.79 5105.52
River Rch & RM=16643,50,11072.97
 1766.69 2420.76 2959.25  3329.2 4860.64 5140.11
River Rch & RM=16643,50,10804.12
 1770.84 2427.44 2968.22 3340.11 4876.56 5157.37
River Rch & RM=16643,50,10337.14
 1778.67 2440.13 2985.31 3360.94 4906.97 5190.49
River Rch & RM=16643,50,10033.24
 1781.19 2444.21  2990.8 3367.62 4916.72 5201.08
River Rch & RM=16643,50,9362.315
 2348.31 3240.72  3981.1 4496.98 6565.59 6712.81
River Rch & RM=16643,50,9140.225
 2358.79 3257.22 4003.02 4523.41 6604.19 6752.24
River Rch & RM=16643,50,8858.665
 2362.02 3262.45 4010.07 4532.01 6616.73 6765.36
River Rch & RM=16643,50,8671.513
 2445.35  3390.9 4178.84  4733.8 6911.35 7059.83
River Rch & RM=16643,50,8299.586
 2447.82 3394.98 4184.39 4740.64 6921.33 7070.38
River Rch & RM=16643,50,8143.534
 2448.92 3396.79 4186.86 4743.67 6925.77 7075.07
River Rch & RM=16643,50, 7932.97
  2451.4 3400.87 4192.42 4750.51 6935.74 7085.61
River Rch & RM=16643,50,7741.143
 2455.24 3407.22 4201.05 4761.13 6951.25    7102
River Rch & RM=16643,50,7539.948
 2459.91 3414.92 4211.53 4774.02 6970.08 7121.88
River Rch & RM=16643,50, 7309.43
 2463.65 3421.14 4220.06 4784.55 6985.44 7138.24
River Rch & RM=16643,50,6993.532
 2466.07 3425.33  4225.9 4791.86 6996.12 7149.91
River Rch & RM=16643,50,6745.941
 3202.87  4501.4  5597.6 6390.91 9330.73 9294.44
River Rch & RM=16643,50,6334.468
 3207.22 4508.86    5608 6403.93 9349.74 9314.44
River Rch & RM=16643,50,6030.548
 3238.78 4561.79 5680.84 6494.36 9481.77 9450.79
River Rch & RM=16643,50,5722.718
 3240.61 4564.93  5685.2 6499.83 9489.75 9459.15
Boundary for River Rch & Prof#=16643,50,1
Up Type= 0
Dn Type= 2
Boundary for River Rch & Prof#=16643,50,2
Up Type= 0
Dn Type= 2
Boundary for River Rch & Prof#=16643,50,2
Up Type= 0
Dn Type= 2
Boundary for River Rch & Prof#=16643,50,2
Up Type= 0
Dn Type= 2
Boundary for River Rch & Prof#=16643,50,2
Up Type= 0
Dn Type= 2
Boundary for River Rch & Prof#=16643,50,2
Up Type= 0
Dn Type= 2

--- 16643_ras.g01 (geometry) ---

Geom Title=16643
Program Version=4.10

River Reach=16643,50
Reach XY= 30
886951.357201815841468.072496868886686.795984003841836.079036926
886759.716102764842006.283010767 886538.86718728842739.575704294
886708.201441306843192.174730708887227.117733018843316.397320035
887057.095510415843614.127027026 887248.11051612843773.879892658
886940.137043067844422.146313563887065.699071125844685.089947013
886716.127442081844761.809386599886423.470032189 844569.07462184
886360.339201725  844789.5813993886287.442227614845228.979449815
886602.536877592845544.691299191 886588.45389941845773.220477302
886388.160331967846658.434412084886142.255023081846845.718595151
886034.139398247847038.357267135886292.670043161847658.526446692
886463.156836519847784.675054053886544.998844359848304.976024401
886368.605588778849263.101221212886103.484724733850076.495165203
886344.847230899850326.510652113887014.788947518850494.071875836
887249.568252021850665.633198769887467.633583423851399.585692912
888354.618271986851929.471772291888528.863594911852174.263690925

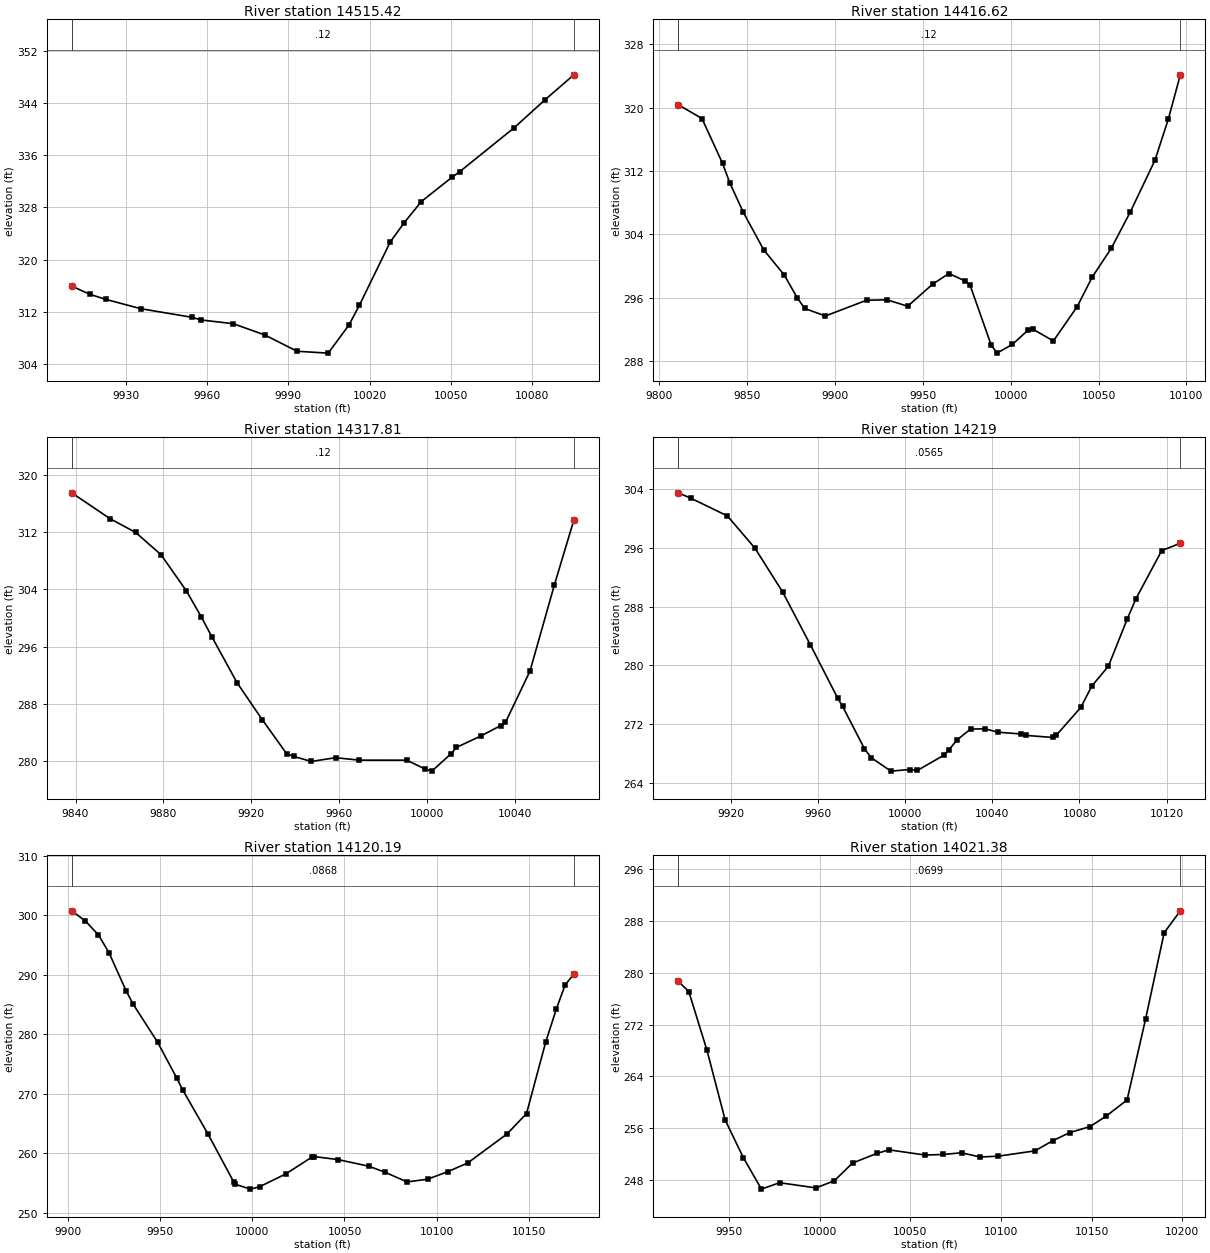
Type RM Length L Ch R = 1 ,14515.42,98.809200,98.809200,98.809200
XS GIS Cut Line= 6
886874.421919647841421.471239642886945.244175518841465.722911506
886949.993952195 841468.44872882886951.733433763841469.435746495
887014.366528605841504.523400176887034.712351387841514.530229663
#Sta/Elev= 20
9910.013315.95339916.673314.70729922.486313.93969935.544 312.4979954.416311.1857
9957.861310.77299969.653310.20849981.444308.46219993.236305.988710004.74 305.705
10012.38309.993710016.21312.991810027.67 322.71910032.85325.685410039.13328.8915
10050.59332.649810053.31333.4625 10073.5340.206210084.64344.396610095.47348.2794
#Mann= 3 , 0 , 0
9910.013    0.12       09910.013    0.12       010095.47    0.12       0
#XS Ineff= 2 , 0
       0                               0
Bank Sta=9910.013,10095.47
Exp/Cntr=0.3,0.1

Type RM Length L Ch R = 1 ,14416.62,98.809300,98.809300,98.809300
XS GIS Cut Line= 6
886733.465866139841449.766618583 886863.05594625841528.550592272
886893.431544373841548.748215269886905.778884829 841557.10427058
886927.006542902 841568.11357791886981.275196288841590.488002339
#Sta/Elev= 30
9810.863320.36499824.362318.62729836.065312.97059840.187310.50729847.768306.8406
9859.471302.06029871.174298.87639878.687295.94979882.877294.64979894.579293.7019
9917.985295.68679929.688295.74199941.391294.93339955.687297.73169964.857299.0625
 9974.17298.11129976.866297.61619988.875290.05549992.231 289.01410000.93290.1079
10010.13291.962310012.97291.9976 10024.3290.547510037.82294.874610046.47298.6336
10057.29302.2616 10068.1306.848210082.12313.374710089.74318.579910096.52324.1402
#Mann= 3 , 0 , 0
9810.863    0.12       09810.863    0.12       010096.52    0.12       0
#XS Ineff= 2 , 0
       09971.314                       0
Bank Sta=9810.863,10096.52
Exp/Cntr=0.3,0.1

Type RM Length L Ch R = 1 ,14317.81,98.809300,98.809300,98.809300
XS GIS Cut Line= 6
 886740.25156255841564.847267386886764.829618214 841579.99805368
886811.488227277841606.916059496 886841.78686936841621.910016039
886876.434813177841636.355148427886942.887950242841669.810319585
#Sta/Elev= 25
9838.293317.55029855.619313.94289867.363 311.9969878.908308.88259890.452303.8103
9897.187 300.1919901.997297.39989913.542290.92179924.951285.76779936.108280.9722
9939.259280.61489947.266279.89619958.319280.42369969.154280.08089990.822 280.076
    9999278.844510002.16278.541910010.99 280.99810013.32281.858510024.49283.4697
10033.48284.922810035.65285.360610046.82292.555310057.98304.690710066.79313.7244
#Mann= 3 , 0 , 0
9838.293    0.12       09838.293    0.12       010066.79    0.12       0
#XS Ineff= 2 , 0
       0                               0
Bank Sta=9838.293,10066.79
Exp/Cntr=0.3,0.1

Type RM Length L Ch R = 1 ,   14219,98.809300,98.809300,98.809300
XS GIS Cut Line= 6
886727.173322118841641.357334951 886786.75055544841687.568912832
886811.154458094841704.383750292886830.139342928841717.139117468
886895.117506223841767.505837277886912.236563933841778.166626356
#Sta/Elev= 30
9895.965303.52599901.909  302.779918.526300.37669931.182295.97079943.837290.0191
9956.493  282.869969.149275.52349971.364 274.425 9981.38268.65989984.468267.4369
 9993.52265.607210002.11265.827710005.63265.695210017.68267.753110020.04268.4756
10023.87269.866310030.02271.3325 10036.7271.373510042.67270.906310053.03270.6754
10055.33270.477210067.98270.189110069.35270.489310080.63274.295610085.67 277.201
10093.28279.911310101.99286.399710105.94289.120410117.73295.659310126.25296.6526
#Mann= 3 , 0 , 0
9895.965  0.0565       09895.965  0.0565       010126.25  0.0565       0
#XS Ineff= 2 , 0
       0                10039.45       0
Bank Sta=9895.965,10126.25
Exp/Cntr=0.3,0.1

Type RM Length L Ch R = 1 ,14120.19,98.809200,98.809200,98.809200
XS GIS Cut Line= 6
886668.963433434841706.714737893886712.745459261841742.798635631
886776.745557975841807.468225424886801.415374835841824.361265065
886824.914663204841835.783471416886889.501720212841857.778834847
#Sta/Elev= 30
9902.233300.74999909.657299.02769916.668296.7091 9922.35293.74669931.784287.2542
9935.564285.04089948.778278.66619959.013272.72039962.245  270.73 9976.04263.2662
9989.995 255.2159990.918 254.823    9999254.012110004.02254.416310018.18256.5589
10032.34259.388610033.41259.4822 10046.5258.974710063.33257.845810072.12256.8285
10083.88255.2238   10095255.671410106.03256.946510116.79258.409810138.13263.2868
10148.65266.711810159.11278.781110164.84284.292610169.58 288.32310174.29 290.113
#Mann= 3 , 0 , 0
9902.233  0.0868       09902.233  0.0868       010174.29  0.0868       0
#XS Ineff= 2 , 0
       0                10035.36       0
Bank Sta=9902.233,10174.29
Exp/Cntr=0.3,0.1

Type RM Length L Ch R = 1 ,14021.38,98.809300,98.809300,98.809300
XS GIS Cut Line= 6
886609.215977986841850.271740795886662.307543052841852.938538983
886718.327159186841848.801170712886774.540357456 841853.55702446
 886824.16342134841860.893108217886883.718791938841873.409660477
#Sta/Elev= 26
9921.957278.70689927.783277.12479937.828268.01889947.833257.27259957.837251.4609
9967.842 246.5789977.858247.57089997.949246.764710008.06247.8762 10018.1250.6113
10031.43252.090310038.12252.6513 10058.2251.845710068.23251.938210078.27252.1988
10088.31251.544610098.42251.669910118.63 252.49210128.74254.0949   10138255.3292
10149.08256.247610157.97257.864810169.51260.369110179.73272.909910189.95286.2112
10198.86289.6049
#Mann= 3 , 0 , 0
9921.957  0.0699       09921.957  0.0699       010198.86  0.0699       0
#XS Ineff= 2 , 0
       0                10040.14       0
Bank Sta=9921.957,10198.86
Exp/Cntr=0.3,0.1

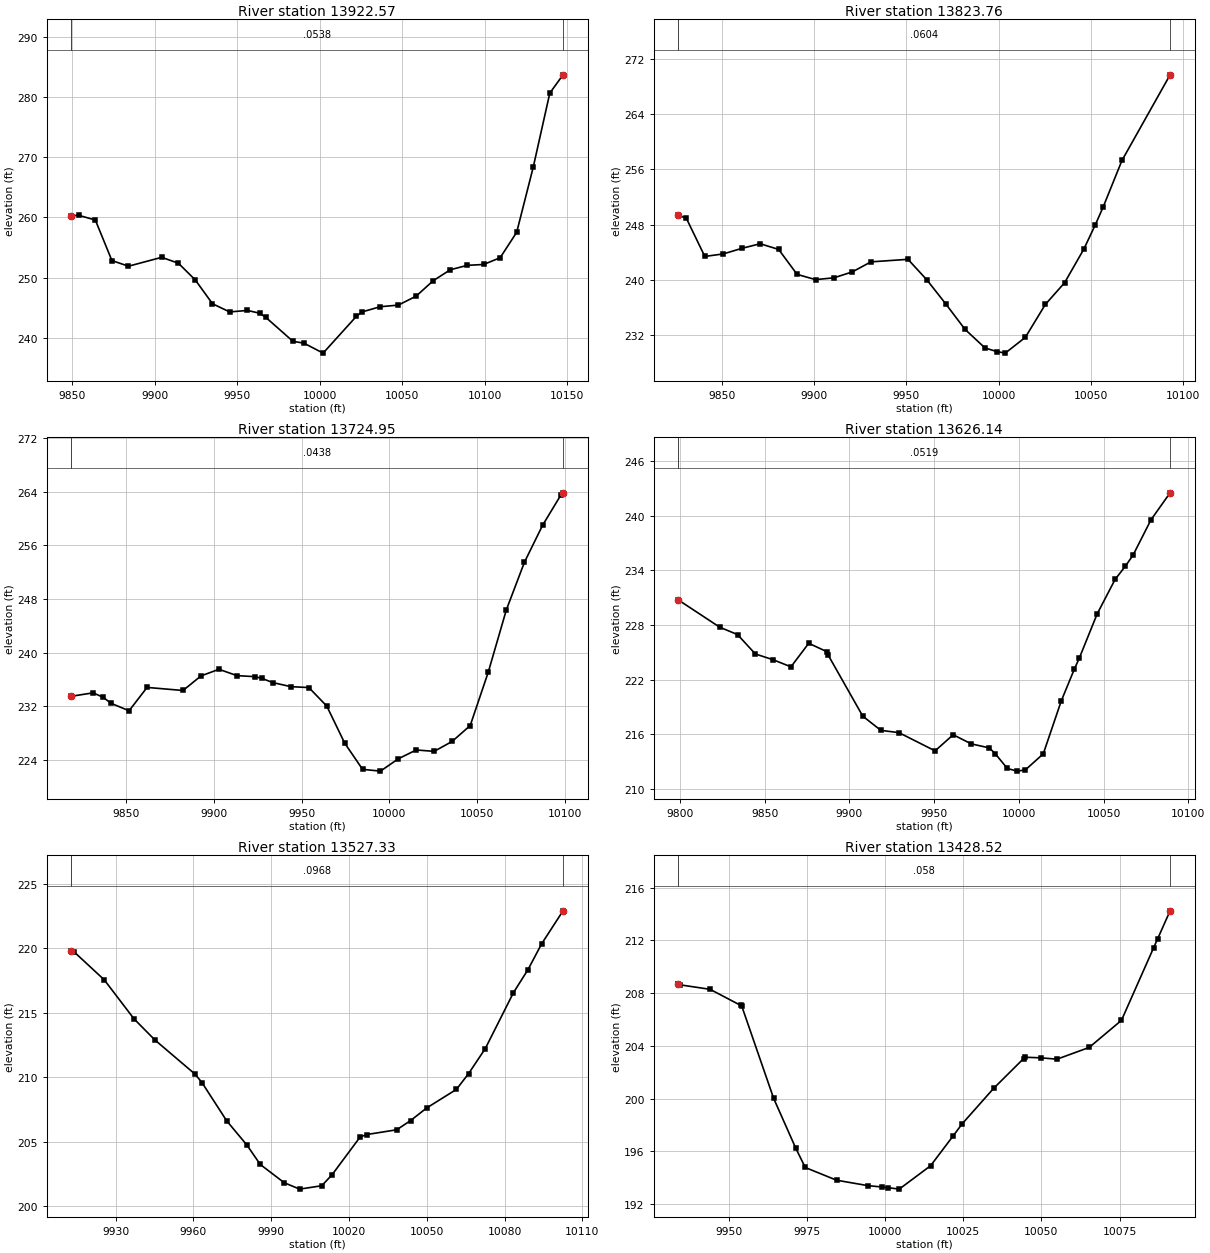
Type RM Length L Ch R = 1 ,13922.57,98.809300,98.809300,98.809300
XS GIS Cut Line= 6
886590.321578772841975.156027748 886636.50343326841972.814908856
886684.731977039841962.079124199886781.605077317841910.868016832
886813.482767341841902.818386238886872.996008261841902.392560058
#Sta/Elev= 30
9849.343 260.3069854.021260.35429864.021259.57849874.049252.8524 9884.08251.9172
9904.233253.39119914.372252.40499924.613249.62429934.994245.68979945.387244.3327
9956.216244.57649963.547244.11839967.153243.46529983.752239.45179990.357239.1544
10002.04237.494710022.21243.604310025.56244.323910036.61245.192410047.63245.4637
10058.41246.949310068.72249.503210079.03251.3157 10089.3252.059510099.32252.2042
10109.33253.327210119.34257.544910129.36268.3425 10139.4280.636610147.42283.6735
#Mann= 3 , 0 , 0
9849.343  0.0538       09849.343  0.0538       010147.42  0.0538       0
#XS Ineff= 2 , 0
       0                10038.07       0
Bank Sta=9849.343,10147.42
Exp/Cntr=0.3,0.1

Type RM Length L Ch R = 1 ,13823.76,98.809200,98.809200,98.809200
XS GIS Cut Line= 6
886580.583357463842006.477490466886708.657879216842013.301320222
886731.796565794842018.670401213886773.577911501842036.955726013
886808.269260186842047.136730451886840.583489428842053.664265215
#Sta/Elev= 27
9826.191249.34619830.611248.90129840.621243.3823 9850.63243.74389860.639244.5464
9870.648245.21799880.657 244.3979890.666240.78979900.675240.02679910.684240.2914
9920.693 241.1549930.714242.5965  9950.8242.96489960.984240.0136 9971.25236.5342
9981.713232.84529992.596 230.141    9999229.627510003.56229.398510014.47231.6824
10025.32236.445110035.74239.576210046.16244.431810052.41 247.96110056.59250.4835
10066.86257.261210092.96269.6456
#Mann= 3 , 0 , 0
9826.191  0.0604       09826.191  0.0604       010092.96  0.0604       0
#XS Ineff= 2 , 0
       0                               0
Bank Sta=9826.191,10092.96
Exp/Cntr=0.3,0.1

Type RM Length L Ch R = 1 ,13724.95,98.809300,98.809300,98.809300
XS GIS Cut Line= 6
886542.764935201 842080.94420965886679.312767373842111.921719007
886719.023732945842119.999252348886720.989034106842120.370185545
886750.813353036842126.492817447886816.328543577842143.032658182
#Sta/Elev= 30
9818.458233.47019831.004233.9871 9836.79233.30769841.258232.41829851.512231.3117
9861.767234.79639882.275234.33719892.529236.51599902.783237.50139913.037236.5563
9923.291236.4043 9927.19236.14749933.545 235.5149943.799234.91039954.053234.7764
 9964.28232.00489974.484226.47919984.689222.56099994.894222.297210005.09224.1406
 10015.3225.457810025.51225.247710035.76226.729410046.08229.099310056.39237.0872
10066.71 246.39110077.02253.494410087.33  258.9910097.65  263.4610099.02263.8523
#Mann= 3 , 0 , 0
9818.458  0.0438       09818.458  0.0438       010099.02  0.0438       0
#XS Ineff= 2 , 0
       0                               0
Bank Sta=9818.458,10099.02
Exp/Cntr=0.3,0.1

Type RM Length L Ch R = 1 ,13626.14,98.809300,98.809300,98.809300
XS GIS Cut Line= 6
886501.625051345842147.712245612886504.499650985842148.486226534
886582.441843846842173.684626315886678.279938368842209.457849067
886692.334416642 842214.44437294886775.628004131842243.759658817
#Sta/Elev= 30
9798.899230.76369823.421227.76089833.931226.9475 9844.44224.8222 9854.95224.1859
9865.459223.40919875.969225.99239886.521225.08619887.552224.65919907.869217.9909
9918.542216.43159929.216216.18129950.564214.17969961.238215.94969971.912214.9494
9982.586214.50369986.087213.86419993.215212.2473    9999211.954810003.83212.0857
10014.43213.852410025.03219.6543 10032.8223.171910035.63224.332710046.23229.2138
10056.83233.003410062.92234.467410067.43235.674910078.03239.5588 10089.3242.5174
#Mann= 3 , 0 , 0
9798.899  0.0519       09798.899  0.0519       0 10089.3  0.0519       0
#XS Ineff= 2 , 0
       0                               0
Bank Sta=9798.899,10089.3
Exp/Cntr=0.3,0.1

Type RM Length L Ch R = 1 ,13527.33,98.809300,98.809300,98.809300
XS GIS Cut Line= 6
886573.880597489842249.164158594886606.232971301842267.380971495
886630.903964623842284.599648022886664.312700919842316.225426126
886699.080997359842336.081327901886732.714409031842349.963802062
#Sta/Elev= 26
9912.893219.80889914.178219.69919925.654217.5608 9937.13214.53459945.169212.8998
9960.713210.23699963.334209.59369972.907206.61529980.682204.74249985.816203.2418
9995.039201.8267   10001201.328510009.52201.592210013.48202.437310024.31205.3696
10026.91205.562910038.43205.930910043.81206.649310049.94207.617410061.46209.0658
10066.16210.293610072.59212.233810083.45216.570310089.01218.341510094.31220.3548
10102.55222.9107
#Mann= 3 , 0 , 0
9912.893  0.0968       09912.893  0.0968       010102.55  0.0968       0
#XS Ineff= 2 , 0
       0                               0
Bank Sta=9912.893,10102.55
Exp/Cntr=0.3,0.1

Type RM Length L Ch R = 1 ,13428.52,98.809200,98.809200,98.809200
XS GIS Cut Line= 6
886554.979764854842381.349384573886591.910522406842388.158315361
886619.495309833842390.348681907 886642.24312844842391.794040979
 886670.18599292842395.815467571886710.074325693842405.994396337
#Sta/Elev= 27
9933.772208.65759933.793208.65759934.371208.62879943.972208.28829953.762207.0702
9954.138206.99829964.303200.02569971.328196.27159974.428194.77379984.459193.8087
9994.491193.3962    9999193.2938   10001193.241210004.51193.132310014.54194.9056
10021.79197.177310024.58198.066310034.68200.7656 10044.3203.032110044.79203.1368
10050.02203.089110054.99202.988510065.31203.881110075.63205.935710085.95211.4578
10087.17212.101410091.19214.2419
#Mann= 3 , 0 , 0
9933.772   0.058       09933.772   0.058       010091.19   0.058       0
#XS Ineff= 2 , 0
       0                               0
Bank Sta=9933.772,10091.19
Exp/Cntr=0.3,0.1

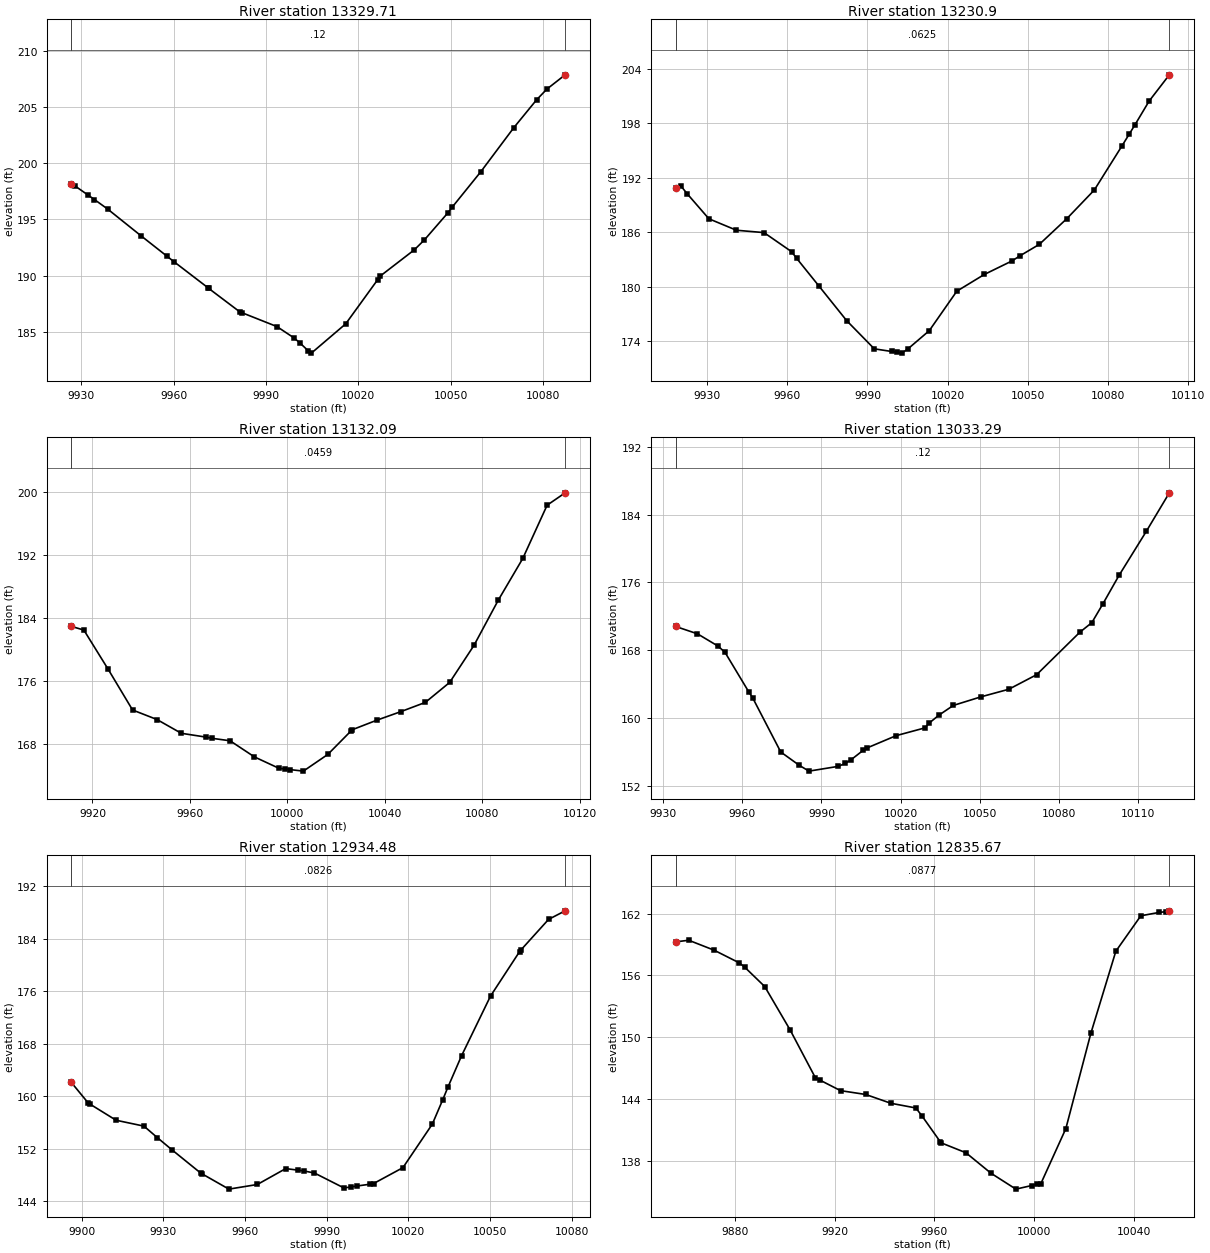
Type RM Length L Ch R = 1 ,13329.71,98.809300,98.809300,98.809300
XS GIS Cut Line= 6
886524.011832408842453.187914374886531.103465906842455.678370945
886565.168530016842470.329077494 886591.63581415842483.754797328
886627.945840931842501.736824912886670.531314355842518.388752062
#Sta/Elev= 29
9926.724198.14259927.771198.00419932.193197.1565 9934.24196.76479938.482 195.928
9949.367193.53959957.834191.71569960.253 191.1959971.139188.91119971.322188.8647
 9981.67186.7256 9982.34186.67229993.546185.4555    9999184.4645   10001 184.006
10003.81183.273310004.75183.090210015.91 185.69810026.34189.644110027.07 189.939
10038.23192.292110041.52193.182210049.09195.571110050.48196.072110059.83199.2436
10070.57 203.17310077.94205.6419 10081.3206.600310087.24 207.873
#Mann= 3 , 0 , 0
9926.724    0.12       09926.724    0.12       010087.24    0.12       0
#XS Ineff= 2 , 0
       0                               0
Bank Sta=9926.724,10087.24
Exp/Cntr=0.3,0.1

Type RM Length L Ch R = 1 , 13230.9,98.809300,98.809300,98.809300
XS GIS Cut Line= 5
886472.902082786842553.957220815886551.250708166842573.656618898
886553.212386093842574.046259395 886637.60415656842594.629551502
886652.452472431842597.226735288
#Sta/Elev= 28
9918.213190.90459920.376191.03289922.489190.25689930.687187.47849940.998186.2164
 9951.31185.95729961.621183.85589963.499183.13229971.932180.04859982.243176.2634
9992.555173.1657    9999172.8765   10001172.791910002.84172.692810005.02 173.129
10013.13 175.16510023.43179.508710033.72181.350310044.01  182.8310047.23183.4327
10054.31184.6652 10064.6 187.49610074.89190.651610085.19195.486910087.87 196.765
10090.02197.791610095.37200.429410102.94203.3223
#Mann= 3 , 0 , 0
9918.213  0.0625       09918.213  0.0625       010102.94  0.0625       0
#XS Ineff= 2 , 0
       0                               0
Bank Sta=9918.213,10102.94
Exp/Cntr=0.3,0.1

Type RM Length L Ch R = 1 ,13132.09,98.809200,98.809200,98.809200
XS GIS Cut Line= 6
886449.874804078842670.819286003886507.491171395842672.683524801
886537.457497847842670.665778427886539.435059744842670.367032975
886564.479097415842668.081343236886652.394808018842665.983933118
#Sta/Elev= 26
9911.319182.88149916.447182.41839926.452177.42279936.458172.25769946.463171.0495
9956.468169.29839966.473168.81859968.966168.66429976.492168.34739986.514166.2941
9996.537164.8541    9999164.7596   10001164.688810006.59164.489510016.63166.6116
10026.15169.593910026.67  169.7510036.67170.951810046.67172.054410056.68173.2221
10066.68175.763410076.68180.481710086.69186.245110096.69191.509310106.69198.2821
10114.09199.8537
#Mann= 3 , 0 , 0
9911.319  0.0459       09911.319  0.0459       010114.09  0.0459       0
#XS Ineff= 2 , 0
       0                               0
Bank Sta=9911.319,10114.09
Exp/Cntr=0.3,0.1

Type RM Length L Ch R = 1 ,13033.29,98.809300,98.809300,98.809300
XS GIS Cut Line= 6
886487.023982375842789.418496686886513.699024209842781.773486491
886535.837708852842773.407284184886579.802167159842753.436635459
886630.600936485842737.103242102886663.457010026 842728.86908643
#Sta/Elev= 28
 9934.76170.80689943.057169.93419950.798168.4933 9953.46167.76079962.509163.0669
  9963.9162.4143 9974.59 155.988 9981.67154.4017 9985.28153.73129996.316154.2916
    9999154.6396   10001155.022710005.82 156.19410007.36156.480310018.29157.9191
10029.22158.8389 10030.6159.354510034.47 160.33810039.93161.485610050.44162.5026
10060.94163.394210071.45165.108310087.83170.122810092.37171.255110096.49173.4351
10102.68176.838810112.99182.028410121.71186.5734
#Mann= 3 , 0 , 0
 9934.76    0.12       0 9934.76    0.12       010121.71    0.12       0
#XS Ineff= 2 , 0
       0                               0
Bank Sta=9934.76,10121.71
Exp/Cntr=0.3,0.1

Type RM Length L Ch R = 1 ,12934.48,98.809300,98.809300,98.809300
XS GIS Cut Line= 6
886488.955415877842886.446415336886519.770405715842879.713567046
886571.579415015842864.335161411886589.237736283842856.863126671
 886620.26753583842844.286334033886660.718034434842829.409179566
#Sta/Elev= 30
9896.236162.09299902.424158.96649903.013158.80969912.659156.33439922.895155.4365
9927.778153.69559933.233151.80789943.665 148.3059944.343148.13759954.096 145.833
9964.527146.53859974.958148.96099979.485148.72719981.822 148.5929985.525148.2867
 9996.35146.0126    9999 146.172   10001146.302510005.96146.584410007.22146.6822
10018.01149.1067 10028.8155.743110032.58159.410710034.48 161.32610039.52 166.146
10050.18175.265510060.83182.027710061.38182.308710071.49186.949910077.58188.2572
#Mann= 3 , 0 , 0
9896.236  0.0826       09896.236  0.0826       010077.58  0.0826       0
#XS Ineff= 2 , 0
       0                               0
Bank Sta=9896.236,10077.58
Exp/Cntr=0.3,0.1

Type RM Length L Ch R = 1 ,12835.67,98.809300,98.809300,98.809300
XS GIS Cut Line= 6
886459.806460395842969.855718456886516.662386779842959.729408271
886564.761787636842954.159306031886603.310722923842952.396592472
886652.235278467842949.420369516886656.356998654842948.720065595
#Sta/Elev= 29
9856.239159.25049861.515159.40649871.672158.44449881.829157.20329883.932 156.797
9891.987154.90859902.144150.70249912.301146.0395 9913.99145.83039922.383144.7909
 9932.45144.42069942.517143.56699952.584143.10659955.103142.31089962.411139.8077
9962.649139.7266 9972.66138.7542 9982.67136.7707 9992.68135.2204    9999135.5688
   10001135.670410002.69135.752610012.71141.104510022.73150.358410032.75158.3395
10042.77161.783310050.01162.107510052.82162.1857 10054.2162.2662
#Mann= 3 , 0 , 0
9856.239  0.0877       09856.239  0.0877       0 10054.2  0.0877       0
#XS Ineff= 2 , 0
       0                               0
Bank Sta=9856.239,10054.2
Exp/Cntr=0.3,0.1

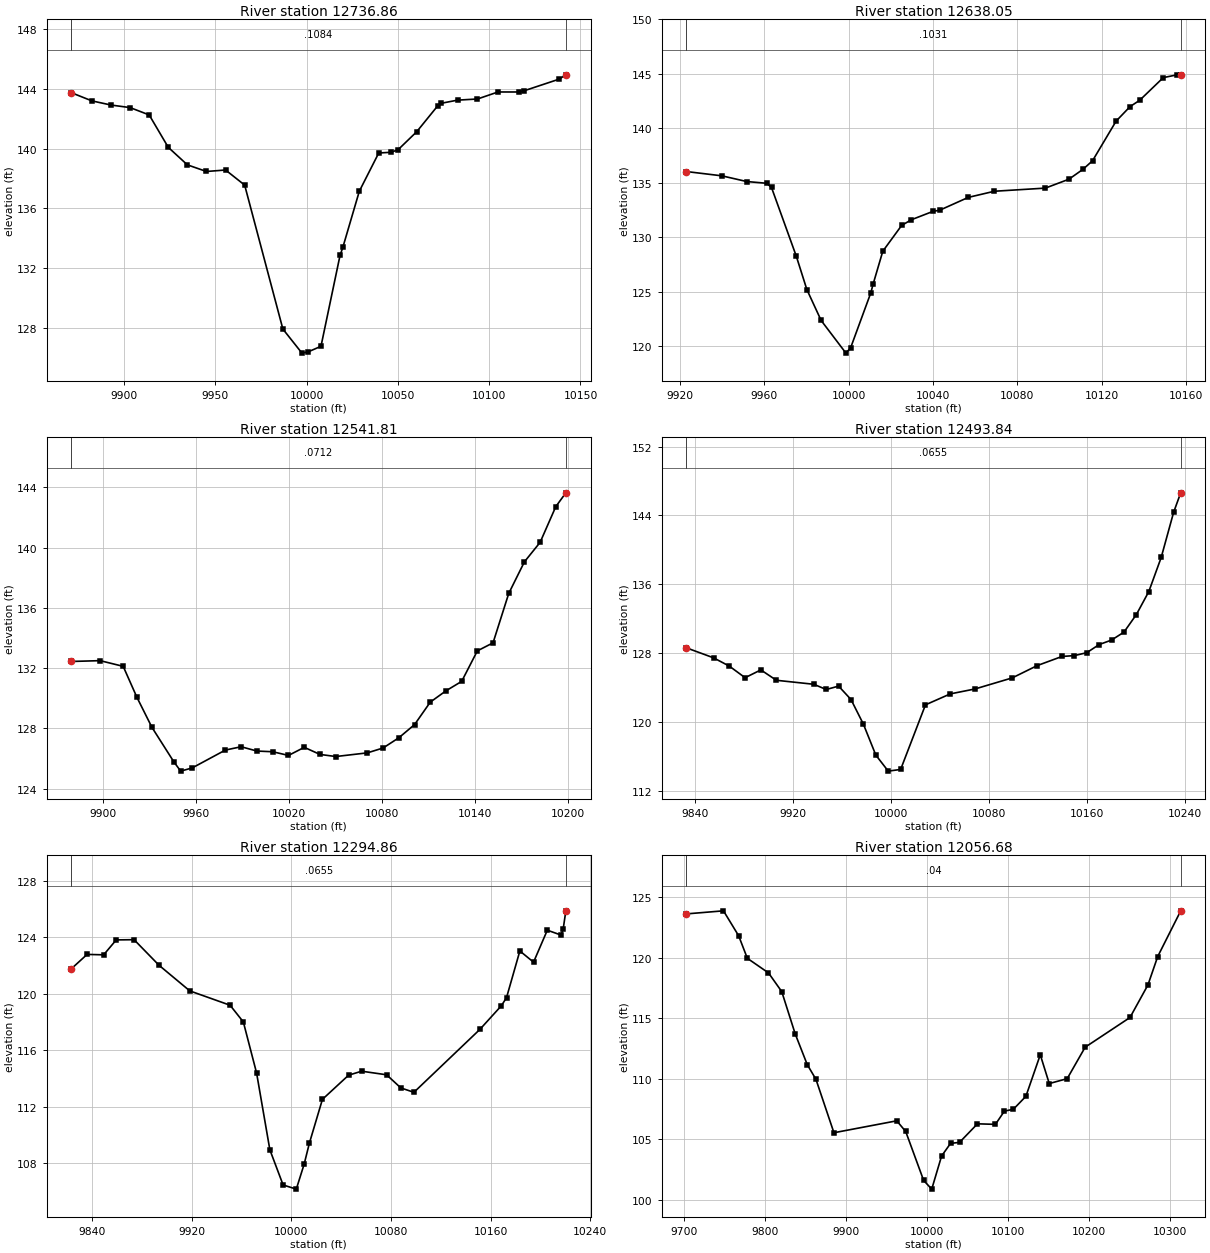
Type RM Length L Ch R = 1 ,12736.86,98.809200,98.809200,98.809200
XS GIS Cut Line= 6
886494.274969044843087.090213762886636.516688903843043.895493178
 886674.57748516843030.291651792886707.679318606843015.598719077
886735.524536525843000.608649772 886746.98935362842992.874001694
#Sta/Elev= 30
9871.247 143.7339882.463143.18899892.921142.91079903.379142.73979913.837142.2507
9924.295140.08419934.753138.91439945.211138.47139955.669138.57059966.126137.5612
9987.042 127.945  9997.5126.3365   10001126.427710007.91126.793410018.33132.8587
10019.91133.415910028.91137.154910039.53139.706810046.33 139.75510050.15139.9277
10060.32141.126410071.73142.842410073.37143.018910082.67143.237610093.61143.3142
10104.85143.783310116.21143.7822 10118.9143.853710138.19 144.63510141.99144.9287
#Mann= 3 , 0 , 0
9871.247  0.1084       09871.247  0.1084       010141.99  0.1084       0
#XS Ineff= 2 , 0
       0                               0
Bank Sta=9871.247,10141.99
Exp/Cntr=0.3,0.1

Type RM Length L Ch R = 1 ,12638.05,96.236600,96.236600,96.236600
XS GIS Cut Line= 6
886600.625616215843175.103022792886666.896622463843134.076919923
886675.927198202843128.390577235886707.635287417843093.463815317
886725.862761191843067.314574318886755.750959357843007.619134605
#Sta/Elev= 29
9923.058  136.039939.964135.63479951.725135.11179961.248  134.959963.487134.5638
9975.248128.24869980.245125.1909 9987.01122.35299998.771119.3501   10001119.8406
10010.58124.894410011.67125.693810016.25128.709410025.17 131.07510029.76131.5989
10040.05132.370410043.26132.479810056.77133.654510069.16134.219310093.31134.5068
10104.49135.323710111.13136.230110115.67137.014610126.86140.660110133.47141.9924
10138.04142.573210149.23144.6566 10155.8 144.91210157.48144.8881
#Mann= 3 , 0 , 0
9923.058  0.1031       09923.058  0.1031       010157.48  0.1031       0
#XS Ineff= 2 , 0
       0                10034.36       0
Bank Sta=9923.058,10157.48
Exp/Cntr=0.3,0.1

Type RM Length L Ch R = 1 ,12541.81,47.973100,47.973100,47.973100
XS GIS Cut Line= 4
886676.978595071843310.585885526886722.890606878843238.946320295
886745.258442224843119.133928146886762.143954411843008.598912716
#Sta/Elev= 30
9879.831132.44229898.343 132.496 9913.23132.11839922.098130.05969931.764 128.072
9945.853125.79059950.297 125.169 9957.73125.38179979.108126.5663 9989.28126.7857
9999.453126.500810009.63126.4544 10019.8126.210410029.97126.746510040.14 126.276
10050.32 126.13710070.66126.381110080.84126.705410090.98127.3838 10101.1128.2576
10111.22129.746310121.33130.494710131.45131.121310141.56133.144210151.68133.6778
 10161.8136.954110171.91139.050910182.03140.343110192.14142.712410198.62143.6264
#Mann= 3 , 0 , 0
9879.831  0.0712       09879.831  0.0712       010198.62  0.0712       0
#XS Ineff= 2 , 0
       09972.108        10055.18       0
Bank Sta=9879.831,10198.62
Exp/Cntr=0.3,0.1

Type RM Length L Ch R = 1 ,12493.84,198.978400,198.978400,198.978400
XS GIS Cut Line= 3
886714.704052069843362.334246988886761.067022933843305.156589151
886814.175431853  842979.2954958
#Sta/Elev= 30
9832.533128.6395 9854.85127.47239867.724126.50859880.599125.16449893.473126.0697
9906.146 124.864  9936.7 124.4019946.832123.79419956.964124.18679967.096122.6276
9977.228119.7621 9987.36116.17539997.492114.315310007.62114.510510027.89122.0124
10048.15123.283910068.42123.859910098.81125.144610119.08126.566210139.34127.6293
10149.47127.7303 10159.6128.068410169.73129.012810179.87129.5348   10190130.4593
10200.13132.498910210.26135.163210220.39139.126810230.53144.366510236.31146.6319
#Mann= 3 , 0 , 0
9832.533  0.0655       09832.533  0.0655       010236.31  0.0655       0
#XS Ineff= 2 , 0
       0 9960.73        10055.89       0
Bank Sta=9832.533,10236.31
Exp/Cntr=0.3,0.1

Type RM Length L Ch R = 1 ,12294.86,238.184000,238.184000,238.184000
XS GIS Cut Line= 6
886891.723307275843384.110127607886922.133852864843346.752110401
 886949.17273429843291.155372882886972.191175235843227.842973407
887011.182615094843104.870713359887045.895651502843021.507886283
#Sta/Elev= 30
9823.541121.76229836.143122.77589849.432122.74589859.538 123.8029873.853123.8175
9893.904122.00599918.597120.19319950.924119.17899961.565117.99599972.206114.3824
9982.847108.95229993.488106.458510004.08106.163710010.39107.932710014.57 109.412
10025.06112.518910046.05114.227310056.54114.509910076.56114.255910088.01113.3262
 10098.5113.015710151.39117.462910168.62119.134510172.82119.711910183.53 123.019
10194.53122.226710205.57124.489510216.61124.144910218.34124.586510220.46125.8602
#Mann= 3 , 0 , 0
9823.541  0.0655       09823.541  0.0655       010220.46  0.0655       0
#XS Ineff= 2 , 0
       0                10048.61       0
Bank Sta=9823.541,10220.46
Exp/Cntr=0.3,0.1

Type RM Length L Ch R = 1 ,12056.68,377.712000,377.712000,377.712000
XS GIS Cut Line= 5
886925.901228856843414.420468322886970.888502299843393.451582747
887022.022467275843374.018015311887069.145786687843359.255805632
887481.498870649843162.794105748
#Sta/Elev= 30
9702.446123.63719748.415123.89189767.177  121.839777.875 119.9699804.019118.7607
9820.382117.21429836.949113.7285 9851.82 111.1879862.649 109.9579884.803105.5499
9962.342106.53579973.419105.65389995.573101.606110005.56100.889510017.73103.6275
 10028.8104.669710039.88 104.75510062.03106.287810084.19106.242810095.27107.3363
10106.34107.4913 10121.8 108.55910139.57 111.99410150.65109.6167 10172.8110.0198
10194.96112.618710250.34115.0752 10272.5117.767610284.55120.112610312.93 123.885
#Mann= 3 , 0 , 0
9702.446    0.04       09702.446    0.04       010312.93    0.04       0
#XS Ineff= 2 , 0
       0                10123.74       0
Bank Sta=9702.446,10312.93
Exp/Cntr=0.3,0.1

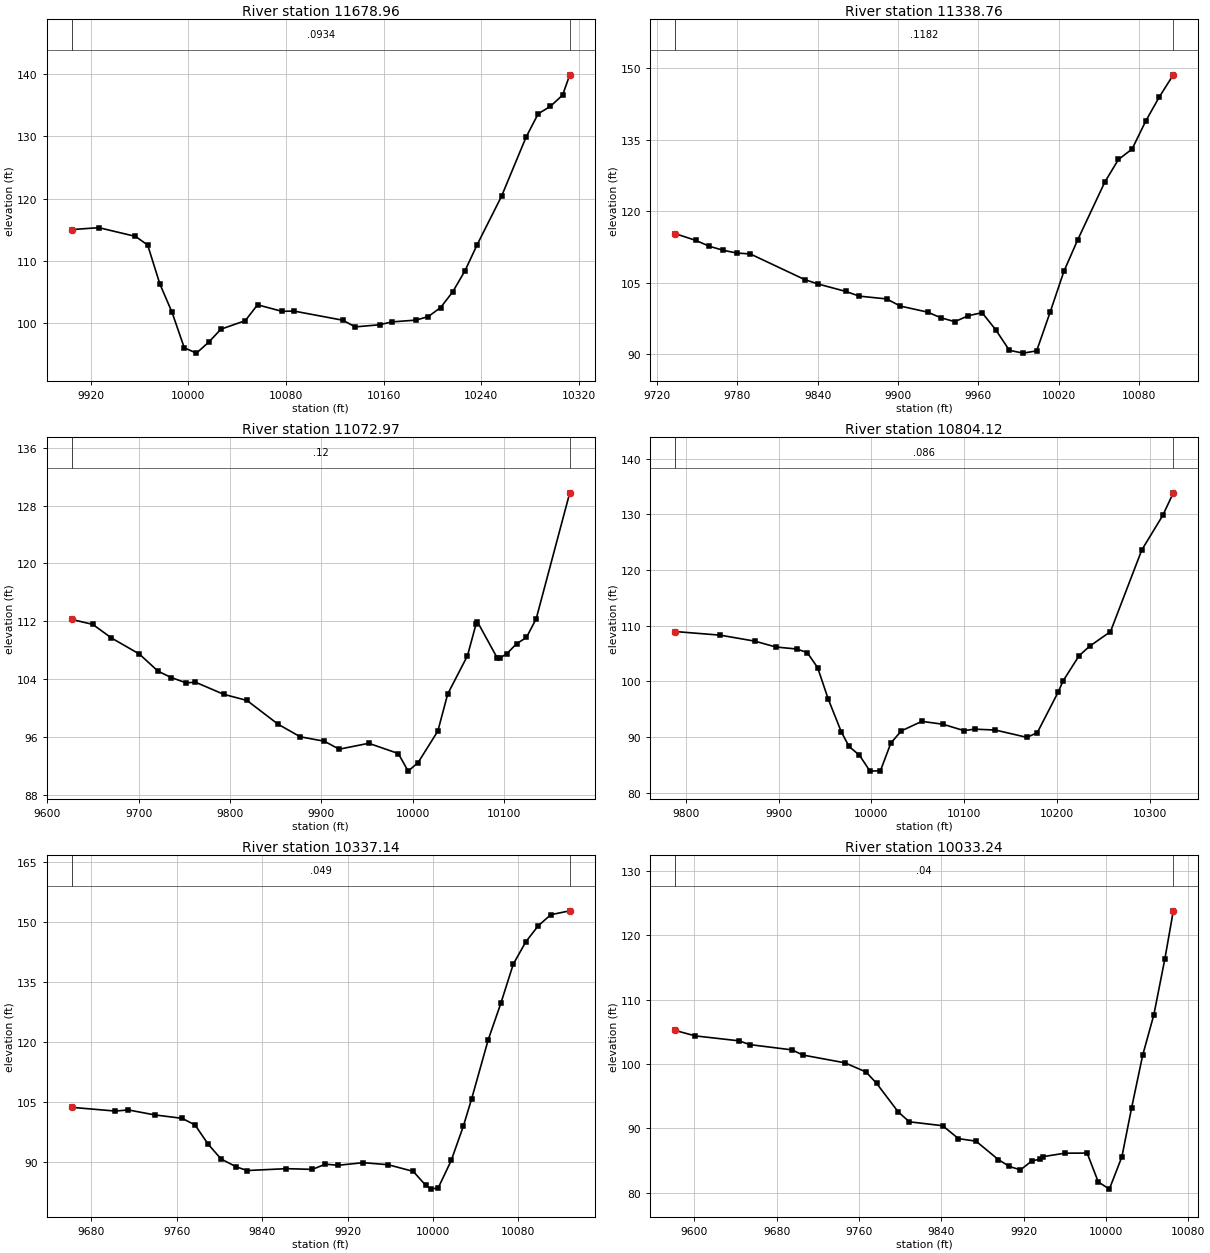
Type RM Length L Ch R = 1 ,11678.96,340.201600,340.201600,340.201600
XS GIS Cut Line= 3
886962.639841517843586.378144087886989.079738324843586.965509678
887370.884142236843596.139834904
#Sta/Elev= 30
9904.213114.98649926.578115.29789956.587 113.892 9966.59112.49579976.593106.2162
9986.596101.63059996.59995.92414 10006.695.07045 10016.696.8320810026.6198.92654
10046.61100.305410056.62102.862510076.62101.810210086.62101.847810126.64100.3714
10136.64 99.299510156.6499.6419210166.65 100.10110186.65 100.39610196.66100.9721
10206.66 102.41110216.66104.956210226.66108.336210236.67112.555710256.67120.3736
10276.68129.860210286.68  133.6610296.69134.855710306.69136.671810312.57139.9402
#Mann= 3 , 0 , 0
9904.213  0.0934       09904.213  0.0934       010312.57  0.0934       0
#XS Ineff= 2 , 0
       0                10196.97       0
Bank Sta=9904.213,10312.57
Exp/Cntr=0.3,0.1

Type RM Length L Ch R = 1 ,11338.76,265.796400,265.796400,265.796400
XS GIS Cut Line= 2
886979.860185705843755.685728946 887345.22829797843825.583893158
#Sta/Elev= 30
9733.521 115.3089748.936113.88279759.117112.65149769.298111.8215 9779.48 111.231
9789.661111.03969830.386105.64289840.568104.7073 9860.93103.17269871.112102.1816
9891.474101.59539901.656100.09659922.01998.82745  9932.297.619589942.38196.82455
9952.563  98.0939962.74498.702469972.92595.113639983.10790.807619993.28890.21807
10003.4790.6893810013.6598.9036710023.83107.393110034.01113.935210054.38126.1376
10064.56130.878610074.74133.063710084.92138.9335 10095.1144.026610105.52148.6451
#Mann= 3 , 0 , 0
9733.521  0.1182       09733.521  0.1182       010105.52  0.1182       0
#XS Ineff= 2 , 0
       0                               0
Bank Sta=9733.521,10105.52
Exp/Cntr=0.3,0.1

Type RM Length L Ch R = 1 ,11072.97,268.844500,268.844500,268.844500
XS GIS Cut Line= 6
886782.261729882843942.508642317886946.135780869843978.101758179
886995.003299127843992.468369463887049.995966465844011.926574317
887223.028320399844083.085892264887299.507230848844111.828387072
#Sta/Elev= 30
 9626.47112.24449649.658111.56039670.053109.68329700.655107.4594 9721.18105.0802
9735.881104.18819751.968103.4698 9762.23103.55359793.018101.8859 9818.64101.0263
9852.70897.737619876.93896.001219903.45395.381429919.64994.280929952.03295.09934
9984.41593.68389 9995.2191.2459610006.0692.4185710027.7196.7858710038.54101.9227
 10060.2107.217710069.47111.553210071.03111.931810092.66106.945210095.91106.9182
10103.36107.506510114.07108.887110124.77 109.74410135.48112.335910172.26  129.77
#Mann= 3 , 0 , 0
 9626.47    0.12       0 9626.47    0.12       010172.26    0.12       0
#XS Ineff= 2 , 0
       0                               0
Bank Sta=9626.47,10172.26
Exp/Cntr=0.3,0.1

Type RM Length L Ch R = 1 ,10804.12,466.982600,466.982600,466.982600
XS GIS Cut Line= 2
886818.697338262844182.584496072887295.087072122844429.700126457
#Sta/Elev= 30
9788.585108.93949837.266108.28539874.543107.20989897.073106.16089919.604105.7995
9930.869105.16439942.135102.4463  9953.496.86373 9967.5790.929139975.93188.29544
9987.19686.724089998.46183.8697710009.7383.9264110020.9988.9128610032.2691.09856
10054.4492.8089910077.3292.2804710099.8591.1382910111.1191.4098510133.65 91.2452
10167.4489.9372110178.7190.7686510201.2498.0758410206.46100.057610223.77104.6004
10235.03106.287610257.56108.922410291.36123.615610313.89129.788110325.25133.8502
#Mann= 3 , 0 , 0
9788.585   0.086       09788.585   0.086       010325.25   0.086       0
#XS Ineff= 2 , 0
       0                               0
Bank Sta=9788.585,10325.25
Exp/Cntr=0.3,0.1

Type RM Length L Ch R = 1 ,10337.14,303.901900,303.901900,303.901900
XS GIS Cut Line= 4
886825.220525304844451.466325398886884.257690308844535.240622345
887000.171722689844616.763967119887190.135953673844732.963659491
#Sta/Elev= 30
9661.352103.56939702.376102.6337 9714.61102.91559739.077101.67829764.747100.8224
9776.97299.181839789.19894.395569801.423 90.6438 9815.57  88.6859825.87487.74165
9862.55188.212939887.00288.034559899.22889.34259 9911.21 89.05999934.655 89.7126
  9958.189.197449981.54587.532739993.26884.03243 9997.9983.0895110004.9983.41471
10017.1590.2601410028.4498.7985610036.32105.732310051.88 120.544 10063.6129.5788
10075.33139.440810087.05145.008510098.77149.050410110.49151.801610128.24152.7694
#Mann= 3 , 0 , 0
9661.352   0.049       09661.352   0.049       010128.24   0.049       0
#XS Ineff= 2 , 0
       0                               0
Bank Sta=9661.352,10128.24
Exp/Cntr=0.3,0.1

Type RM Length L Ch R = 1 ,10033.24,670.922700,670.922700,670.922700
XS GIS Cut Line= 4
 886664.11299744844366.640275003886689.284788893844436.226821236
886718.491175935844564.130207831886823.872505256844822.564486347
#Sta/Elev= 30
9581.256 105.212 9600.78104.36459643.317103.59689653.951103.00589695.027 102.186
9705.284101.39239746.314100.17579766.82898.752759777.08696.99081 9798.1992.52699
9808.98991.002559841.38790.395769856.65888.389949873.78687.991259895.385 85.1386
9906.18484.064959916.98383.529779927.78384.89232 9936.1185.215469938.58285.58052
9960.18186.12554 9981.7886.140569992.57981.6622610003.3880.5364610015.56 85.5616
10024.98 93.148810035.78101.364410046.58107.613910057.38116.379110065.55 123.811
#Mann= 3 , 0 , 0
9581.256    0.04       09581.256    0.04       010065.55    0.04       0
#XS Ineff= 2 , 0
       0                               0
Bank Sta=9581.256,10065.55
Exp/Cntr=0.3,0.1