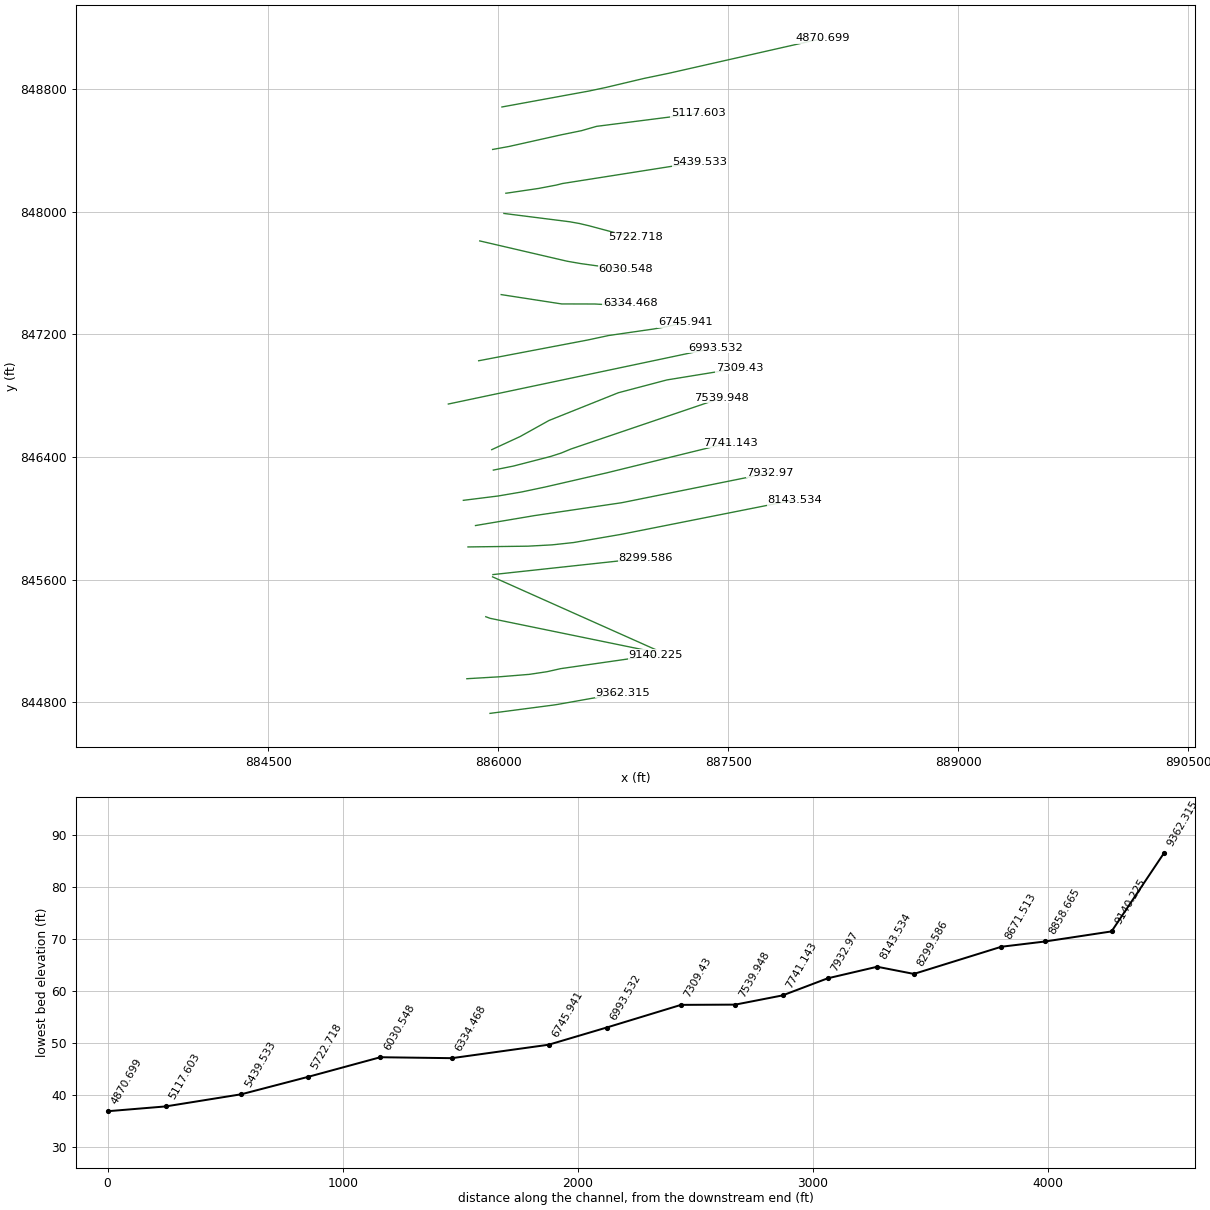
HEC-RAS study 16643_ras.prj: 16643

--- 16643_ras.g01 (geometry) --- (continued)

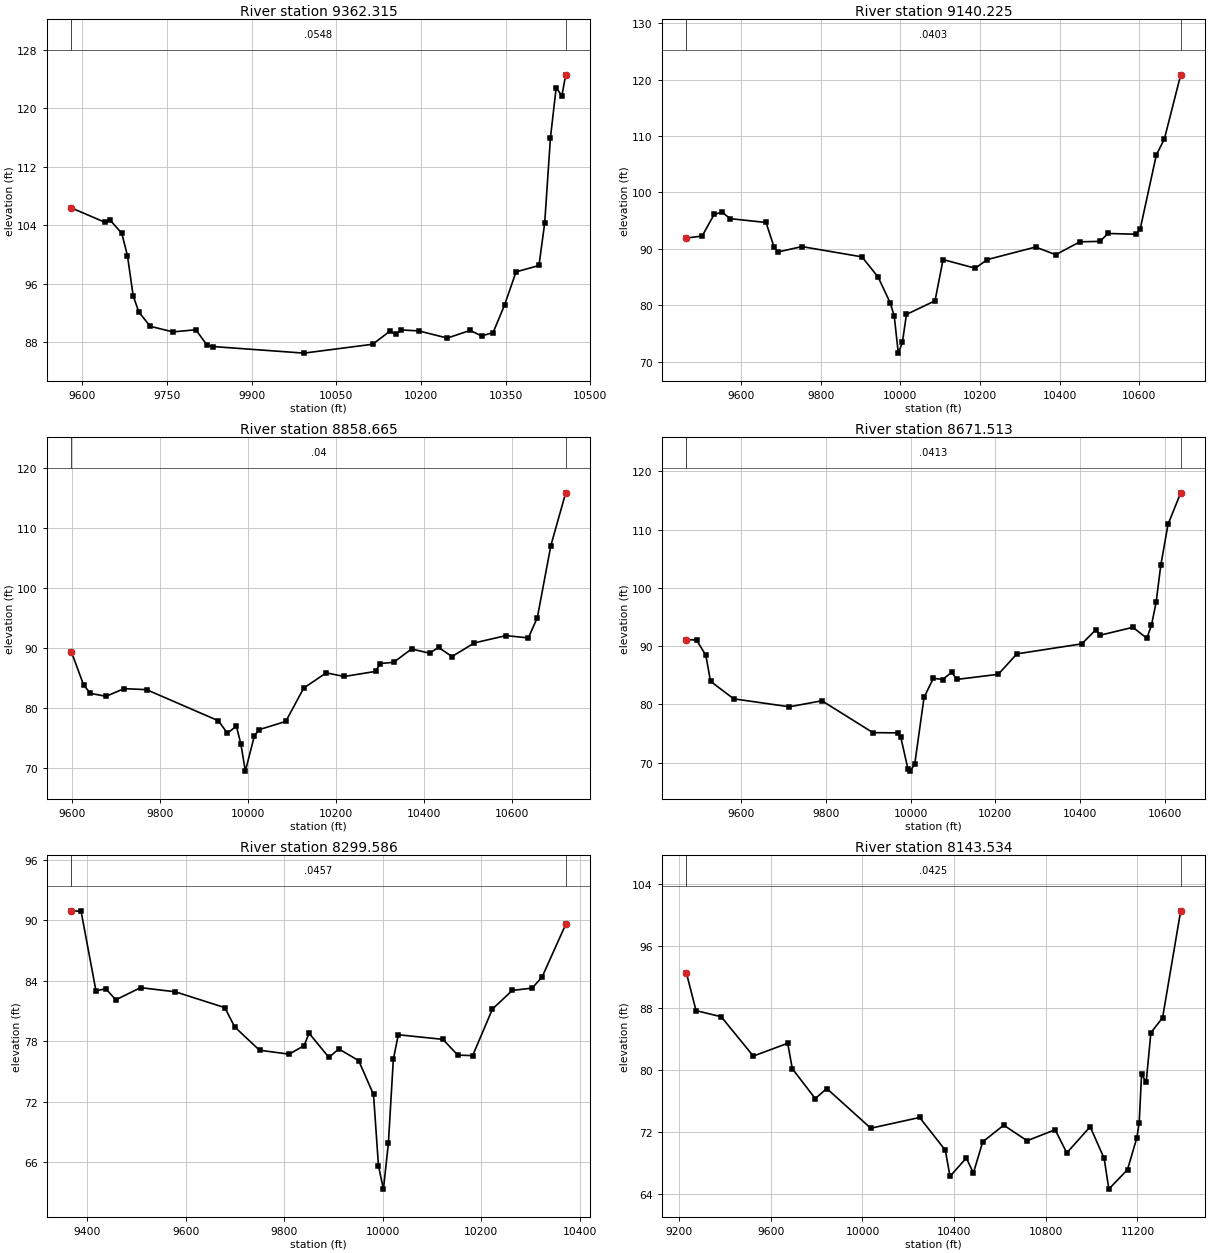
Type RM Length L Ch R = 1 ,9362.315,222.089600,222.089600,222.089600
XS GIS Cut Line= 6
885946.485763606844727.842505289886358.015701717844781.779752791
886380.646010655 844785.12445605886382.622946086844785.427346026
886418.905795305844791.805838347886811.614439084 844861.81470567
#Sta/Elev= 30
9580.769106.36059639.783104.40889649.869104.6443 9670.04102.88789680.12699.81792
9690.21194.346329700.29792.117119720.46890.17131 9760.8189.408129801.152 89.7014
9821.32387.582919831.40887.408419992.77786.5055710114.5187.7211910144.9989.50545
10155.1489.12464 10165.389.6724710195.7789.5488410246.6788.5662710287.1989.60966
10307.51 88.853510327.8289.3207610348.1493.0836410368.4597.6140610409.08 98.4878
10419.24 104.298 10429.4115.967510439.56122.788210449.72121.695310456.43124.5568
#Mann= 3 , 0 , 0
9580.769  0.0548       09580.769  0.0548       010456.43  0.0548       0
#XS Ineff= 2 , 0
       09883.763        10160.22       0
Bank Sta=9580.769,10456.43
Exp/Cntr=0.3,0.1

Type RM Length L Ch R = 1 ,9140.225,281.559800,281.559800,281.559800
XS GIS Cut Line= 6
885795.388030834844953.795436172886009.951311546844966.542918263
886202.181496862844982.203153156886318.620363552 844999.64721218
886407.530118442845019.599629189887025.582485326845108.381862368
#Sta/Elev= 30
9462.72991.883019502.41192.255639532.464 96.09539552.49996.469529572.53495.33205
9662.69394.653339682.73290.329279692.75789.426159752.90890.375979903.65488.55602
9944.06784.980469974.49880.409169984.64178.047589994.814 71.491910005.0373.38086
10015.2678.35126   10087 80.768210107.2188.0774810188.0386.5418810218.3488.07751
10339.5790.3019410390.0888.94121 10450.791.2263910501.2191.3048110521.42  92.705
10592.1392.5683210602.2493.5134510642.65106.619510662.85109.448610703.85120.8292
#Mann= 3 , 0 , 0
9462.729  0.0403       09462.729  0.0403       010703.85  0.0403       0
#XS Ineff= 2 , 0
       0                10174.94       0
Bank Sta=9462.729,10703.85
Exp/Cntr=0.3,0.1

Type RM Length L Ch R = 1 ,8858.665,187.152100,187.152100,187.152100
XS GIS Cut Line= 3
885918.986573245845358.102303786885946.688996756845347.772234917
 887018.09348739845128.015577409
#Sta/Elev= 30
9597.99289.412219625.75583.888589641.35582.488079676.87582.007899717.707 83.2778
9768.74883.114659932.07977.934529952.49675.872699972.91277.03693 9983.1274.07376
9993.32869.5596210013.7475.4050110023.9576.44011 10085.277.8320110126.0383.38023
10177.0885.9098210217.91 85.301310289.3786.1504310299.5787.46042 10330.287.65613
10371.0389.8779510411.8689.1785310432.2890.13647 10462.9  88.62310513.9590.89023
 10585.492.1013310636.4491.7215610656.86 95.107910687.49107.060410721.27115.8533
#Mann= 3 , 0 , 0
9597.992    0.04       09597.992    0.04       010721.27    0.04       0
#XS Ineff= 2 , 0
       0 9866.05        10270.55       0
Bank Sta=9597.992,10721.27
Exp/Cntr=0.3,0.1

Type RM Length L Ch R = 1 ,8671.513,371.927600,371.927600,371.927600
XS GIS Cut Line= 2
885963.018293508845618.167694819887027.929899659845142.797042229
#Sta/Elev= 30
9471.20591.112789495.27791.02515 9517.1888.387659528.13183.944269582.88680.94573
  9714.379.579589790.95780.61264 9911.4275.138169969.62375.105629977.12674.32929
9994.15668.821549999.02868.5395310009.9869.7556210031.8881.1783310053.7884.47685
10075.6984.2617810097.5985.5130910108.5484.26882 10207.185.15287 10250.988.66011
10404.2290.3786210437.07  92.79610448.0291.8725410524.6893.2154210557.5391.34204
10568.4993.5902610579.4497.5071710590.39103.850110607.46110.8703 10637.4116.2933
#Mann= 3 , 0 , 0
9471.205  0.0413       09471.205  0.0413       0 10637.4  0.0413       0
#XS Ineff= 2 , 0
       09791.362                       0
Bank Sta=9471.205,10637.4
Exp/Cntr=0.3,0.1

Type RM Length L Ch R = 1 ,8299.586,156.052100,156.052100,156.052100
XS GIS Cut Line= 2
885965.437416004845632.922038357886962.749143889845740.916220417
#Sta/Elev= 30
9368.00590.943359387.68290.898239417.85883.002459437.97583.204759458.09282.10588
9508.38483.314699578.79382.904029679.37881.330059699.49579.411569749.78777.10071
9810.13876.710959840.31377.570499850.37178.789679890.605 76.38559910.72277.23271
9950.956 76.06919981.13172.70835 9991.1965.6325410001.2563.3103810011.3167.86534
10021.3776.2020210031.4278.6376710121.9578.1811410152.1376.61535 10182.376.56608
10222.5381.1949110262.7783.04073   1030383.2690710323.1284.3640910371.1589.59045
#Mann= 3 , 0 , 0
9368.005  0.0457       09368.005  0.0457       010371.15  0.0457       0
#XS Ineff= 2 , 0
       09839.409        10041.81       0
Bank Sta=9368.005,10371.15
Exp/Cntr=0.3,0.1

Type RM Length L Ch R = 1 ,8143.534,210.563900,210.563900,210.563900
XS GIS Cut Line= 6
885802.846169486 845813.22182414886194.698111334845818.210542165
886352.491499279845826.849010583886491.237289628845841.878103582
886803.259905086845895.588104871887932.645432377 846119.71366056
#Sta/Elev= 30
9231.49192.507449273.64987.659149383.65786.867269523.66981.807779673.72483.45731
9693.74380.18995    979476.337069844.29277.6334210036.3172.5269710249.5873.90995
10361.7269.6915410382.1166.3333810453.4868.7020310484.0666.7514810524.8470.77448
 10616.672.9162410718.5570.9178510840.8972.3287710891.8669.3505310993.8172.71944
11054.9868.6400211075.3764.6899911156.9367.2092111197.7171.3117411207.9173.24977
 11218.179.4508111238.4978.4691711258.8884.8195811309.8686.7343911389.02100.4978
#Mann= 3 , 0 , 0
9231.491  0.0425       09231.491  0.0425       011389.02  0.0425       0
#XS Ineff= 2 , 0
       09857.679         10175.4       0
Bank Sta=9231.491,11389.02
Exp/Cntr=0.3,0.1

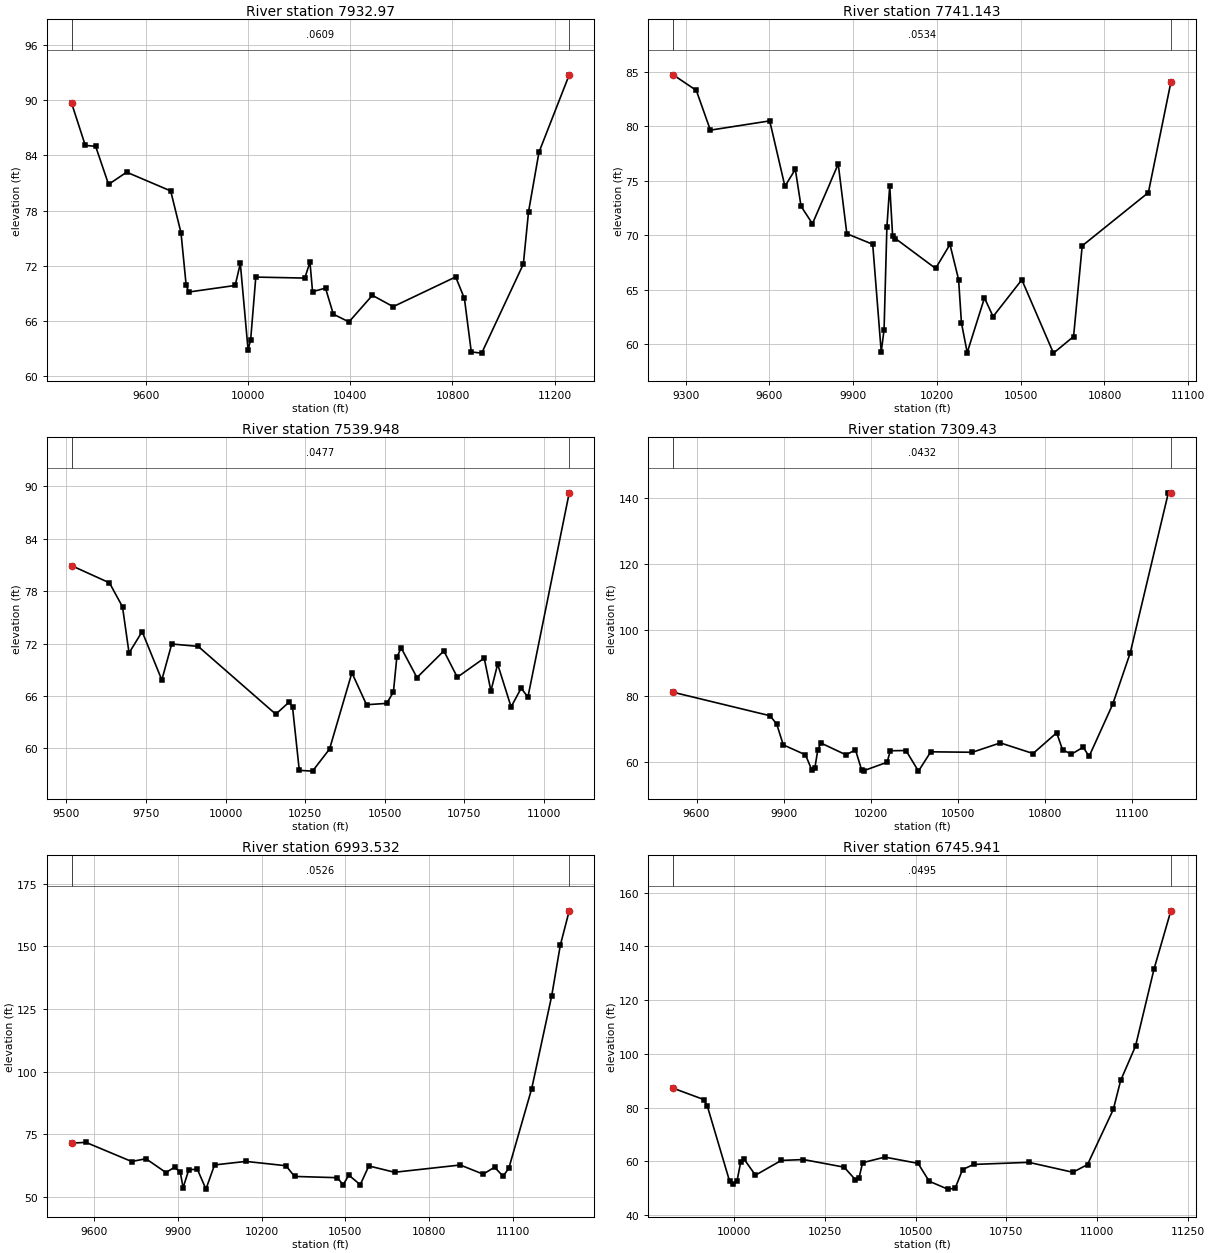
Type RM Length L Ch R = 1 , 7932.97,191.826600,191.826600,191.826600
XS GIS Cut Line= 4
885851.961531957845952.760347555886238.381740036846017.837772257
886805.396116985846101.623329874887771.289660446846296.070406853
#Sta/Elev= 30
9307.27789.708589361.06285.091049401.62584.99316 9452.3380.847869523.31582.17236
9695.70980.133639736.15475.578319756.37269.87087 9766.48 69.11999948.43569.83474
9968.65272.234399998.97862.8525410009.0963.89896 10029.370.7471910221.3770.63965
10241.5872.3887110251.6969.1572810302.5169.5463910333.11 66.710910394.3165.86477
10486.1268.7615110567.7267.5252310812.5470.7636510846.7968.4225910873.74 62.5917
10914.5562.4642111077.7572.1642211098.1677.8711111138.96  84.34211257.5892.77834
#Mann= 3 , 0 , 0
9307.277  0.0609       09307.277  0.0609       011257.58  0.0609       0
#XS Ineff= 2 , 0
       0 9865.69        10345.84       0
Bank Sta=9307.277,11257.58
Exp/Cntr=0.3,0.1

Type RM Length L Ch R = 1 ,7741.143,201.195300,201.195300,201.195300
XS GIS Cut Line= 6
885772.654322317846117.164963787885997.781542207846145.199836999
886151.848671867846171.479555565886304.317152914846203.608703665
 886706.15445117846295.978076377887513.428513905846494.193476873
#Sta/Elev= 30
9255.17584.739149338.03583.308269388.38479.657529600.974 80.50879655.42874.49761
9692.67476.059149713.11372.669359753.99171.061149846.35476.541889877.24170.14386
9969.88669.1730410000.3859.2825210010.5361.3274310020.6870.7605210030.86 74.5604
10041.1269.9725510051.3869.6987310195.1366.9561210246.5869.1593910277.47 65.9353
10287.77  61.94810308.3659.2209710370.1564.2475410401.0462.5349510504.0165.91448
10617.2759.1758210689.3560.6977110720.2569.0333710957.34 73.924711037.8384.05658
#Mann= 3 , 0 , 0
9255.175  0.0534       09255.175  0.0534       011037.83  0.0534       0
#XS Ineff= 2 , 0
       09874.049        10438.27       0
Bank Sta=9255.175,11037.83
Exp/Cntr=0.3,0.1

Type RM Length L Ch R = 1 ,7539.948,230.518000,230.518000,230.518000
XS GIS Cut Line= 6
885968.221674893846314.317257584886098.543286299846340.495903653
886342.145925839846403.345903801886411.580430473846425.868030036
886473.965496938846451.737526261887457.915816303846785.667155344
#Sta/Elev= 30
9515.88180.910139634.98778.944849676.02276.203379696.59170.913569737.72873.36546
9799.58967.830079830.73171.946549913.94671.6724910157.7563.9133310199.9765.30566
10210.5464.6844210231.6757.4884710273.2357.3996110326.7759.9254110397.0468.64756
10443.0164.9985710506.4165.1509410527.5466.4554610538.1170.4037710551.8171.50584
10601.51 68.102910686.0471.1534710728.3168.1458310812.8470.3268310833.9766.57371
 10855.169.6376410897.3764.7480410929.0766.89046 10950.265.8704711080.0889.24336
#Mann= 3 , 0 , 0
9515.881  0.0477       09515.881  0.0477       011080.08  0.0477       0
#XS Ineff= 2 , 0
       09837.859        10439.54       0
Bank Sta=9515.881,11080.08
Exp/Cntr=0.3,0.1

Type RM Length L Ch R = 1 , 7309.43,315.898300,315.898300,315.898300
XS GIS Cut Line= 6
885957.527845563846447.473088262  886142.6871965846533.014309242
886331.394387659846637.979701696886782.862414119846818.556920634
887099.822532354846902.262280917887573.582297922846979.421459536
#Sta/Elev= 30
9519.61381.191389853.21874.097849876.28371.571749898.89965.290219975.47862.27857
9996.77757.7808410007.4858.1799610018.1163.8907410028.7565.8414410114.9262.27867
10147.6363.7776510169.4457.5510910176.2557.4850210256.6760.0372210267.5863.50863
10321.7163.5840710364.6257.3541610407.15 63.190410550.4163.0569310646.6965.88712
10759.4362.6751110840.8268.9443910861.1763.7919310891.6962.47873 10932.3 64.5839
10952.5761.7996611033.56  77.507 11094.293.0758811225.57141.474111234.24141.4663
#Mann= 3 , 0 , 0
9519.613  0.0432       09519.613  0.0432       011234.24  0.0432       0
#XS Ineff= 2 , 0
       09783.896        10412.08       0
Bank Sta=9519.613,11234.24
Exp/Cntr=0.3,0.1

Type RM Length L Ch R = 1 ,6993.532,247.590800,247.590800,247.590800
XS GIS Cut Line= 2
885674.605085864846745.152328136887416.361516137847112.731481309
#Sta/Elev= 30
9520.32771.389879571.83271.682959735.35664.037479786.45765.149639857.99959.62377
 9888.6661.743329909.10159.824599919.32153.564899939.76160.790289970.42260.90726
10001.0852.9966510031.7462.6692510144.1764.0822710287.2562.3506810317.9158.07334
10471.21 57.565110491.66 54.6886 10512.158.5824910552.9854.7568810583.6462.26391
10675.6259.7366410910.69 62.640310992.4558.9844511033.3361.7368811063.9958.15033
11084.4361.3727311166.1993.1631411237.73130.2376 11268.4150.438511300.45 164.252
#Mann= 3 , 0 , 0
9520.327  0.0526       09520.327  0.0526       011300.45  0.0526       0
#XS Ineff= 2 , 0
       0 9952.31        10608.16       0
Bank Sta=9520.327,11300.45
Exp/Cntr=0.3,0.1

Type RM Length L Ch R = 1 ,6745.941,411.472400,411.472400,411.472400
XS GIS Cut Line= 6
 885872.46269367847027.312662038 886579.64565761 847161.86002799
886720.391717032847191.963304407 887011.39918404847234.080230325
887093.921278945847248.795603335887219.845196818847277.607806458
#Sta/Elev= 30
 9832.4187.238099916.44783.037269926.62880.510929987.71852.66552  9997.951.44731
10008.0852.5649510018.26 59.647910028.4460.7124110058.9954.8643410130.2660.36181
10191.35 60.687310303.3557.8538310333.8953.2310810344.08 53.705910354.26 59.5164
10415.35 61.600810506.9559.2690310537.4152.6365510588.5249.6789110609.0549.98067
10629.5756.9592410660.1658.8736910812.1659.6454310933.3355.9565110973.7258.80958
11044.7379.3301111065.0490.1195711105.92 102.895 11157.1131.673911203.31153.2708
#Mann= 3 , 0 , 0
 9832.41  0.0495       0 9832.41  0.0495       011203.31  0.0495       0
#XS Ineff= 2 , 0
       0                10674.01       0
Bank Sta=9832.41,11203.31
Exp/Cntr=0.3,0.1

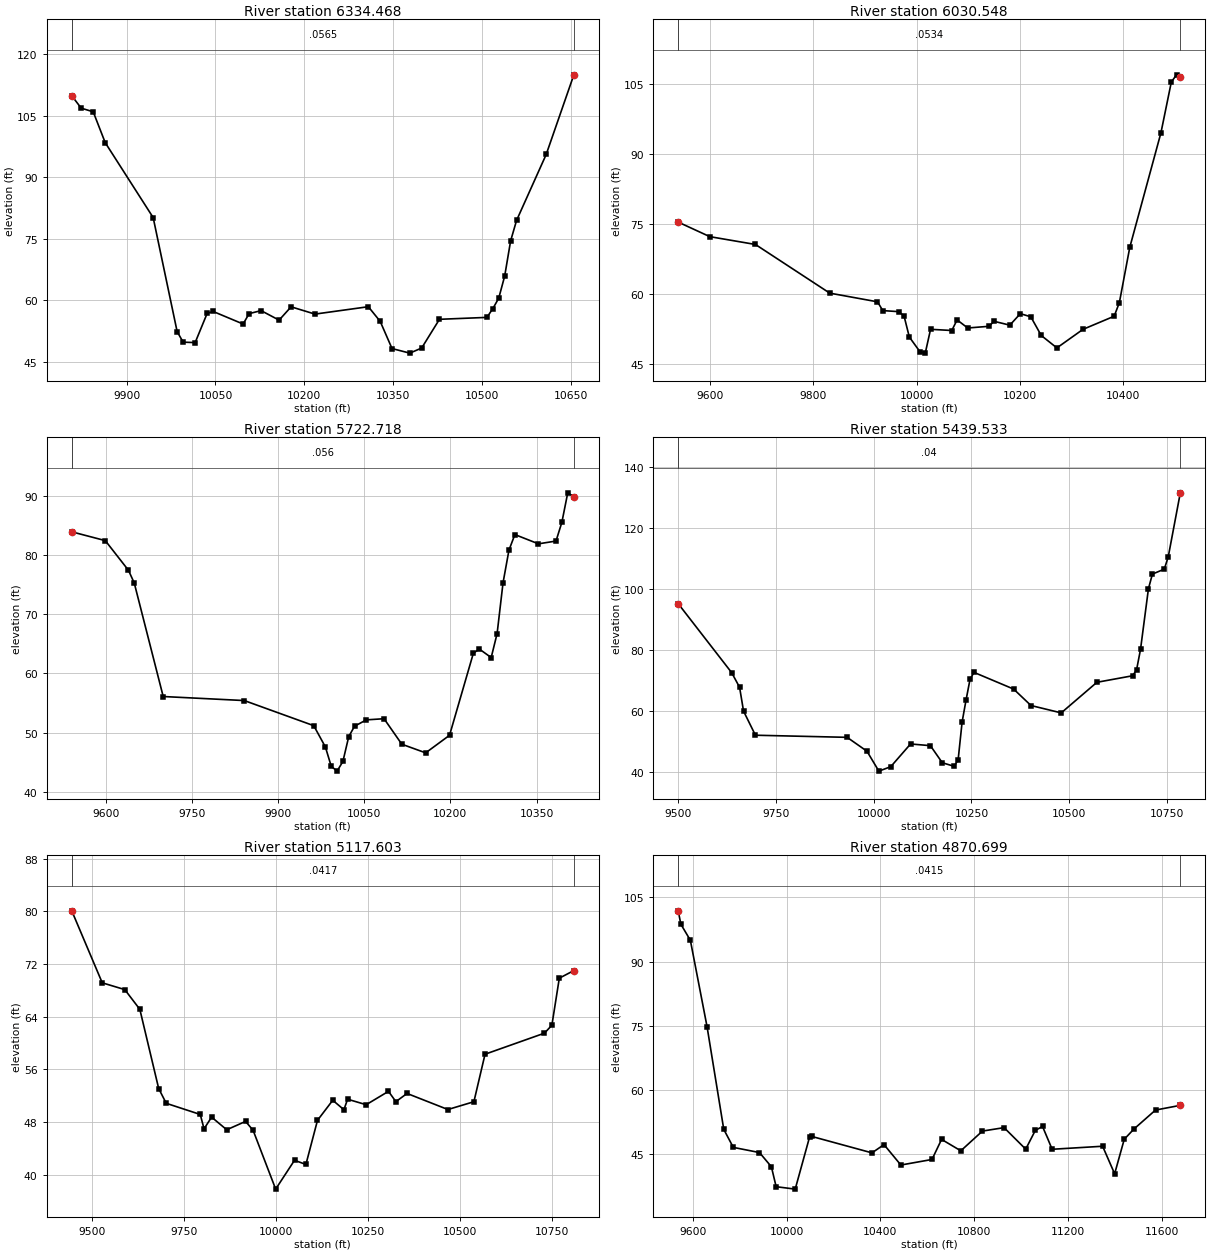
Type RM Length L Ch R = 1 ,6334.468,303.920500,303.920500,303.920500
XS GIS Cut Line= 6
886019.248812024 847458.73188158886413.412693704847397.902567554
886629.797995765847397.441387547886676.231735048847394.883749496
886734.562048988 847395.65677458 886861.56161694847401.860546614
#Sta/Elev= 30
9807.514109.81859823.452106.79289843.689105.91279863.92598.396849944.87280.13071
9985.346  52.3229995.46449.76916 10015.749.6593810035.9456.7750310046.0657.25023
10096.6554.1848910106.7756.72588   1012757.4524310157.3655.13416 10177.658.38147
10217.9356.6066110307.9358.4065910327.9354.8361510347.9348.2054510377.9347.09448
10397.9348.3368410427.9455.3376810508.0155.8033510518.0157.9353310528.0160.49738
10538.0265.8803110548.0374.4469210558.04 79.4272 10608.195.5283510654.72114.9199
#Mann= 3 , 0 , 0
9807.514  0.0565       09807.514  0.0565       010654.72  0.0565       0
#XS Ineff= 2 , 0
       0                10514.38       0
Bank Sta=9807.514,10654.72
Exp/Cntr=0.3,0.1

Type RM Length L Ch R = 1 ,6030.548,307.829500,307.829500,307.829500
XS GIS Cut Line= 6
885879.525156568847808.832611779886448.664702825847676.549926327
886538.832815781847660.885340088886642.796861867 847646.46465856
886757.465286507847633.979479782886832.338939585847627.345692189
#Sta/Elev= 30
9538.82775.376949599.92772.259339688.17970.583959831.91160.14619 9924.3158.28043
9934.57656.397359965.37656.173059975.64355.247169985.909 50.725110006.4447.58045
10016.7147.2752310026.9852.3849110068.0452.1283610078.3154.4065310098.8452.66675
10139.7253.0269610149.8754.1004210180.3253.2723710200.6255.7406810220.8855.07143
10241.07 51.062110271.3548.3944210321.8352.3752310382.1955.1922610392.2558.12604
10412.3669.9607510472.6494.5324510492.72105.419410502.76106.972210510.13106.5142
#Mann= 3 , 0 , 0
9538.827  0.0534       09538.827  0.0534       010510.13  0.0534       0
#XS Ineff= 2 , 0
       0                               0
Bank Sta=9538.827,10510.13
Exp/Cntr=0.3,0.1

Type RM Length L Ch R = 1 ,5722.718,283.185200,283.185200,283.185200
XS GIS Cut Line= 6
886037.112343843847987.982077872886465.424552212847933.810867342
886528.595322863847922.558927048886591.465650742847907.787061847
886812.408778178847848.665341237886895.409824208847831.749690498
#Sta/Elev= 30
9541.06383.890049599.41282.404549639.73177.39414 9649.8175.251929700.20956.08519
9841.32455.40381 9962.2851.163639982.51447.565969992.67144.3140810002.8343.48973
10012.9945.1185510023.14 49.3131 10033.351.07234 10053.852.1440210084.6252.33788
10115.5748.0312210157.0746.5750710198.6149.5407210240.14 63.415510250.51  64.094
10271.1262.6644610281.4266.7199610291.7375.2843810302.03 80.798410312.3483.42643
10353.3381.8616110383.9482.3321810394.1585.5046510404.3690.4731210414.9889.79365
#Mann= 3 , 0 , 0
9541.063   0.056       09541.063   0.056       010414.98   0.056       0
#XS Ineff= 2 , 0
       0                               0
Bank Sta=9541.063,10414.98
Exp/Cntr=0.3,0.1

Type RM Length L Ch R = 1 ,5439.533,321.929900,321.929900,321.929900
XS GIS Cut Line= 6
886049.991157675848119.812811239 886065.53114473848121.873773767
886262.064765585848150.869249831886378.567292477  848172.9976184
886418.400450891848183.029566339 887315.39377896848324.350417489
#Sta/Elev= 30
9501.18795.057089637.62572.449299657.84267.64469 9667.9559.830679698.27551.92486
9932.48551.231039983.10146.6771310013.4740.1487510043.8441.6049610094.4649.05845
10145.0748.4997910175.4442.9019110205.8141.7242510215.9443.9106910226.0656.26003
10236.1863.5093710246.3170.2720710256.4372.5353210357.6767.0584110401.89 61.6696
10479.1559.2486410570.2669.2828210661.3771.4270110671.4973.3301710681.6180.06852
10701.8699.9743310711.98104.777810742.35 106.39910752.48110.472110783.24131.4271
#Mann= 3 , 0 , 0
9501.187    0.04       09501.187    0.04       010783.24    0.04       0
#XS Ineff= 2 , 0
       0                               0
Bank Sta=9501.187,10783.24
Exp/Cntr=0.3,0.1

Type RM Length L Ch R = 1 ,5117.603,246.904000,246.904000,246.904000
XS GIS Cut Line= 6
 885963.63719855848405.323415583886070.603754296848424.790910593
886404.814795764848499.465364003886542.775118207848527.695134272
886641.798982178 848555.99961944887304.122447249848640.353730385
#Sta/Elev= 30
9445.83280.064289528.53269.133549589.71668.104229630.60465.103999681.71353.08274
9702.20650.838389794.57749.145189804.84146.961049825.36848.739859866.42146.82122
9917.61748.092249938.02446.735299999.24637.8080410050.4242.1901810081.32 41.5521
10112.7848.25786 10154.251.2990810184.4449.8708410194.5251.4600910244.92 50.6247
10305.41 52.655910325.5751.0875910355.8152.33544 10466.7 49.894910537.2751.07741
10567.5158.29197 10728.861.4891410748.9662.6973710769.1269.8385210808.5670.99408
#Mann= 3 , 0 , 0
9445.832  0.0417       09445.832  0.0417       010808.56  0.0417       0
#XS Ineff= 2 , 0
       0                10170.64       0
Bank Sta=9445.832,10808.56
Exp/Cntr=0.3,0.1

Type RM Length L Ch R = 1 ,4870.699,246.904100,246.904100,246.904100
XS GIS Cut Line= 6
886024.164017407848682.266791898886593.146490941848786.490147155
886700.465414309 848809.18778436886951.201114121848868.588918001
887107.746852245848900.986541675888118.226686572 849129.90239238
#Sta/Elev= 30
9538.168101.88329549.19598.76645  9589.995.005999661.13474.815999732.36750.84053
9773.04646.631119884.74745.42316 9935.5242.10692 9955.8337.4490610037.1436.88108
10098.1749.0009210108.3449.1793910364.5845.3516610415.9647.2775210487.8742.50996
10620.6343.8069210661.5548.4973610743.5845.8330610835.8650.4398610928.1451.24393
11020.4246.2177511061.4350.5985311092.1951.52063 11133.246.1895811348.5346.89669
11399.7940.4629911440.8148.5292611481.82 50.9029 11574.155.3504511679.9456.44792
#Mann= 3 , 0 , 0
9538.168  0.0415       09538.168  0.0415       011679.94  0.0415       0
#XS Ineff= 2 , 0
       0                 10305.5       0
Bank Sta=9538.168,11679.94
Exp/Cntr=0.3,0.1