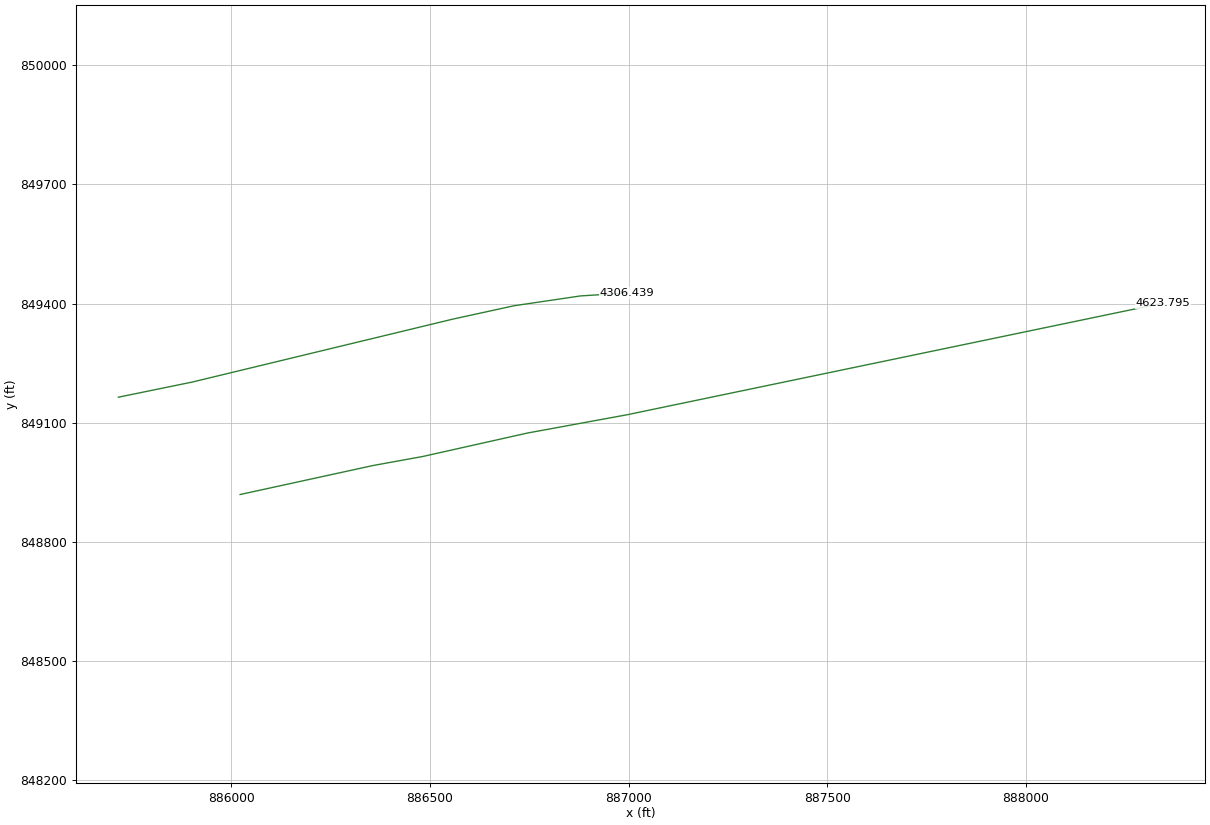
HEC-RAS study 16643_ras.prj: 16643

--- 16643_ras.g01 (geometry) --- (continued)

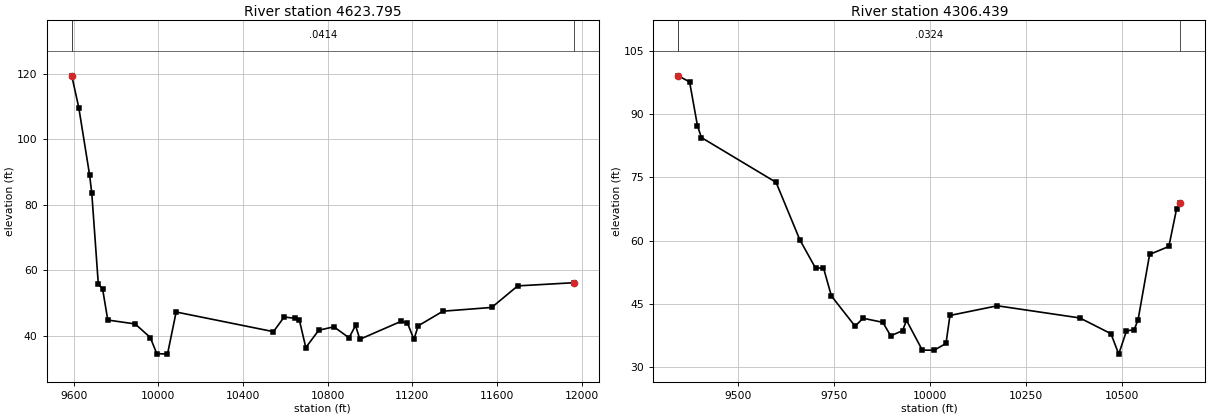
Type RM Length L Ch R = 1 ,4623.795,317.355800,317.355800,317.355800
XS GIS Cut Line= 6
886022.397901047848919.410670685886357.136983523848992.437746637
886481.688870297849015.036734636886745.700590617849074.193779862
886996.012654537849120.118234636888344.694406762849401.050673218
#Sta/Elev= 30
9591.124119.39399624.441109.63479675.53889.049879685.75783.505999716.42755.90382
9736.91554.303779761.20244.858489890.57643.671669962.06639.526939992.56434.62679
10043.3734.4576410084.2247.3132710543.8641.3145710594.5945.8039910645.6645.37597
10666.0944.9051710696.7436.4599710758.0341.7544110829.5342.7916410901.0339.44116
10931.6743.19743 10952.1 38.986211146.1844.4459811176.8343.9406511207.4738.98121
 11227.943.1018611344.9247.56369 11575.248.7049311697.7755.2847611963.0456.25222
#Mann= 3 , 0 , 0
9591.124  0.0414       09591.124  0.0414       011963.04  0.0414       0
#XS Ineff= 2 , 0
       0                10474.36       0
Bank Sta=9591.124,11963.04
Exp/Cntr=0.3,0.1

Type RM Length L Ch R = 1 ,4306.439,0.000000,0.000000,0.000000
XS GIS Cut Line= 6
885715.978383241849164.311115682885902.530129434849202.560404487
886558.156233146849360.943532177886712.562861526849394.608367877
 886879.11986179849419.197330169886994.751541024849426.464406557
#Sta/Elev= 30
9345.09299.098289374.64997.659179395.07487.308969405.28784.469119599.81573.83866
9661.55660.230979702.71753.476079723.29753.531659743.87846.887029805.61939.71803
  9826.241.603799877.65140.638959898.23137.445659929.10238.650169939.39241.11061
9980.55334.0353110011.4234.0306510042.2635.6212210052.5442.2690110175.9344.56037
10390.8241.6749210471.8237.9303510491.9833.0951710512.1438.58242 10532.338.90773
10542.3541.2495810572.4156.7429610622.5258.6315410642.5667.5143310652.3268.87441
#Mann= 3 , 0 , 0
9345.092  0.0324       09345.092  0.0324       010652.32  0.0324       0
#XS Ineff= 2 , 0
       0                               0
Bank Sta=9345.092,10652.32
Exp/Cntr=0.3,0.1